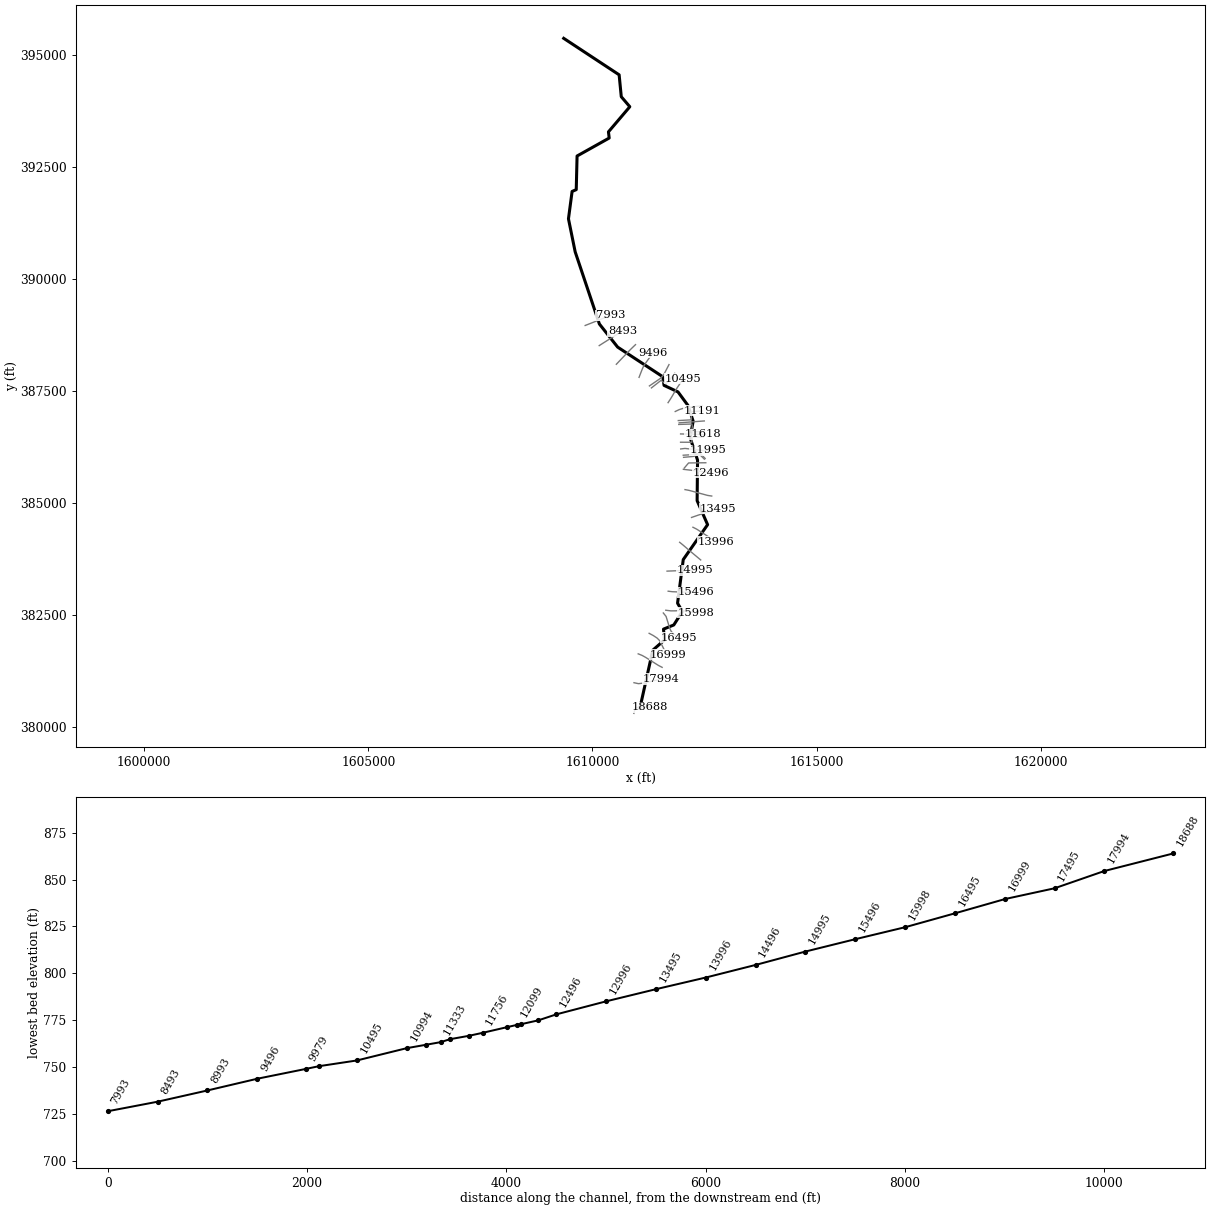
--- STATERN.prj (project) ---

Proj Title=STATERN
Current Plan=p01
Default Exp/Contr=0,0
English Units
Geom File=g01
Flow File=f01
Plan File=p01
BEGIN DESCRIPTION:
---------- MODELED AS PART OF WVEMD CTP PROGRAM, 2023----------
Stream Name:State Run
Flood Zone:  AFH
Wetzel County, WV
HEC-RAS Version: RAS 6.3
Vertical Datum: NAVD88
Projection: NAD 1983 StatePlane West Virginia S FIPS 4702 (US Feet)
Terrain: 1-meter West Virginia FEMA R3 South Central (collected 2018-2020)
Land Use: 2019 NLCD
Hydrologic Method:
WV SIR2010-5033 regression equations
Additional Model Notes:
Leveraged XS
END DESCRIPTION:
DSS Export Rating Curves= 0
DSS Export Rating Curve Sorted= 0
DSS Export Volume Flow Curves= 0
DXF OffsetX= 0
DXF OffsetY= 0
DXF ScaleX= 0
DXF ScaleY= 0

--- STATERN.p01 (plan) ---

Plan Title=Floodplain
Program Version=6.30
Short Identifier=Floodplain
Geom File=g01
Flow File=f01
Subcritical Flow
K Sum by GR= 0
Std Step Tol= 0.01
Critical Tol= 0.01
Num of Std Step Trials= 20
Max Error Tol= 0.3
Flow Tol Ratio= 0.001
Split Flow NTrial= 30
Split Flow Tol= 0.02
Split Flow Ratio= 0.02
Log Output Level= 0
Friction Slope Method= 1
Unsteady Friction Slope Method= 2
Unsteady Bridges Friction Slope Method= 1
Parabolic Critical Depth
Global Vel Dist= 0 , 0 , 0
Global Log Level= 0
CheckData=True
Encroach Param=-1 ,0,0, 0
Mapping Interval=1HOUR
Computation Time Step Use Courant=        0
Computation Time Step Use Time Series=    0
Computation Time Step Count To Double=0
Computation Time Step Max Doubling=0
Computation Time Step Max Halving=0
Computation Time Step Residence Courant=0
Run HTab= 0
Run UNet= 0
Run Sediment= 0
Run PostProcess= 0
Run WQNet= 0
Run RASMapper=-1
UNET Theta= 0
UNET Theta Warmup= 0
UNET ZTol= 0
UNET ZSATol= 0
UNET MxIter= 0
UNET Max Iter WO Improvement= 0
UNET MaxInSteps= 0
UNET DtIC= 0
UNET DtMin= 0
UNET MaxCRTS= 0
UNET WFStab= 0
UNET SFStab= 0
UNET WFX= 1
UNET SFX= 1
UNET Gravity=32.17405
UNET 1D Methodology=Finite Difference
UNET DSS MLevel= 1
UNET Pardiso=0
UNET DZMax Abort= 0
UNET Use Existing IB Tables= 0
UNET Froude Reduction=False
UNET Froude Limit= 0
UNET Froude Power= 0
UNET D1 Cores= 0
UNET WindReference=Eulerian
UNET WindDragFormulation=Hsu (1988)
UNET D2 Coriolis=0
UNET D2 Cores= 0
UNET D2 Theta= 1
UNET D2 Theta Warmup= 1
UNET D2 Z Tol= 0.01
UNET D2 Volume Tol= 0.01
UNET D2 Max Iterations= 20
UNET D2 Equation= 0
UNET D2 RampUpFraction=0.1
UNET D2 TimeSlices= 1
UNET D2 Turbulence Formulation=Non-Conservative (original)
UNET D2 Eddy Viscosity=0.3
UNET D2 Transverse Eddy Viscosity=0.1
UNET D2 Smagorinsky Mixing=0
UNET D2 BCVolumeCheck=0
UNET D2 Cores=0
UNET D2 SolverType=PARDISO (Direct)
UNET D2 Minimum Iterations= 3
UNET D2 Maximum Iterations= 30
UNET D2 Restart Number= 10
UNET D2 Relaxation Coeff=1.3
UNET D2 SOR Precondition Iterations= 10
UNET D2 ILUT Maximum Fill= 8
UNET D2 ILUT Tolerance=1E-08
UNET D2 Convergence Tolerance=0.00001
UNET D1D2 MaxIter= 0
UNET D1D2 ZTol=0.01
UNET D1D2 QTol=0.1
UNET D1D2 MinQTol=1
Write IC File= 0
Write IC File at Fixed DateTime=0
Write IC File at Sim End=0
Echo Input=False
Echo Parameters=False
Echo Output=False
Write Detailed= 0
HDF Write Warmup=0
HDF Write Time Slices=0
HDF Flush=0
HDF Compression= 1
HDF Chunk Size= 1
HDF Spatial Parts= 1
HDF Use Max Rows=0
HDF Fixed Rows= 1
Calibration Method= 0
Calibration Iterations= 20
Calibration Max Change=0.05
Calibration Tolerance=0.2
Calibration Maximum=1.5
Calibration Minimum=0.5
Calibration Optimization Method= 1
WQ AD Non Conservative
WQ ULTIMATE=-1
WQ Max Comp Step=1HOUR
WQ Output Interval=15MIN
WQ Output Selected Increments= 0
WQ Output face flow=0
WQ Output face velocity=0
WQ Output face area=0
WQ Output face dispersion=0
WQ Output cell volume=0
WQ Output cell surface area=0
WQ Output cell continuity=0
WQ Output cumulative cell continuity=0
WQ Output face conc=0
WQ Output face dconc_dx=0
WQ Output face courant=0
WQ Output face peclet=0
WQ Output face adv mass=0
WQ Output face disp mass=0
WQ Output cell mass=0
WQ Output cell source sink temp=0
WQ Output nsm pathways=0
WQ Output nsm derived pathways=0
WQ Create Restart=0
WQ Fixed Restart=0
WQ System Summary=0
WQ Write To DSS=0
Sorting and Armoring Iterations= 10
XS Update Threshold= 0.02
Bed Roughness Predictor= 0
Hydraulics Update Threshold= 0.02
Energy Slope Method= 1
Volume Change Method= 1
Sediment Retention Method= 0
Sediment TS Multiplier= 1
Warm Up Method= 0
XS Weighting Method= 0
Number of US Weighted Cross Sections= 1
Number of DS Weighted Cross Sections= 1
Upstream XS Weight=0
Main XS Weight=1
Downstream XS Weight=0
Number of DS XS's Weighted with US Boundary= 1
Upstream Boundary Weight= 1
Weight of XSs Associated with US Boundary= 0
Number of US XS's Weighted with DS Boundary= 1
Downstream Boundary Weight= 0.5
Weight of XSs Associated with DS Boundary= 0.5
Percentile Method= 0
Sediment Output Level= 3
Mass or Volume Output= 0
Output Increment Type= 1
Profile and TS Output Increment= 1
Transport Output Increment 1
XS Output Flag= 0
XS Output Increment= 10
Read HDF5 Sediment Hotstart= 0
Sediment Hotstart Type= 0
Write Gradation File= 0
Read Gradation Hotstart= 0
Write HDF5 File= 1
Write Binary Output= 1
Write DSS Sediment File= 0
DSS Sediment Output Type= 1
SV Curve= 0
Specific Gage Flag= 0
Subcell Erosion Methods= 0
Subcell Deposition Methods= 0
Advection Scheme= 1
Matrix Solver= 0
Implicit Weighting Factor= 1
Maximum Outer Loop Convergence Iterations= 5
Convergence Maximum Absolute= 0.001
Convergence RMSE= 0.0001
Grain Fractions Max Abs Error= 0.001
Max Subgrid Regions= 1
Max Subgrid Length Scale= 3.402823E+38
Initial Layer Thickness= 3.402823E+38
Min Layer Thickness= 3.402823E+38
Max Layer Thickness= 3.402823E+38
Number of Layers= 5

--- STATERN.f01 (steady flow) ---

Flow Title=Flow
Program Version=6.30
Number of Profiles= 1
Profile Names=F01pct
River Rch & RM=STATERN,Main,18688
     626
River Rch & RM=STATERN,Main,17994
     702
River Rch & RM=STATERN,Main,15998
     792
River Rch & RM=STATERN,Main,14995
     924
River Rch & RM=STATERN,Main,12496
    1030
River Rch & RM=STATERN,Main,11618
    1160
River Rch & RM=STATERN,Main,8493
    1340
River Rch & RM=STATERN,Main,6994
    1490
Boundary for River Rch & Prof#=STATERN,Main            , 1
Up Type= 0
Dn Type= 3
Dn Slope=0.00881
DSS Import GetInterval= 0
DSS Import GetPeak= 0
DSS Import FillOption= 0

--- STATERN.g01 (geometry) ---

Geom Title=Geometry
Program Version=6.30

River Reach=STATERN         ,Main
Reach XY= 30
1611058.47028339 380410.901925091611346.47128339 381706.81692509
1611608.87928339 381937.899925091611585.77128339 382177.71392509
1611815.31428339 382270.659925091612006.34328339 382571.58192509
1611899.53128339 382756.961925091612026.37028339 383730.07992509
1612569.67328339 384509.600925091612336.02128339 385045.20092509
1612345.26528339 385951.560925091612179.91228339 386449.15992509
1612247.18328339 386819.920925091612131.64128339 387170.65392509
1611909.80128339 387472.602925091611598.09528339 387618.95592509
1611570.87928339 387811.011925091610562.84228339 388473.45092509
1610155.81528339 388989.182925091609615.40128339 390600.95692509
1609465.96728339 391337.342925091609547.10328339 391948.42992509
1609639.53628339 391988.484925091609658.02328339 392739.24892509
1610374.38128339 393140.306925091610357.94828339 393278.44292509
1610834.49328339 393839.204925091610643.97828339 394062.58592509
1610596.28557824394551.4989701811609359.98383081395365.964597274

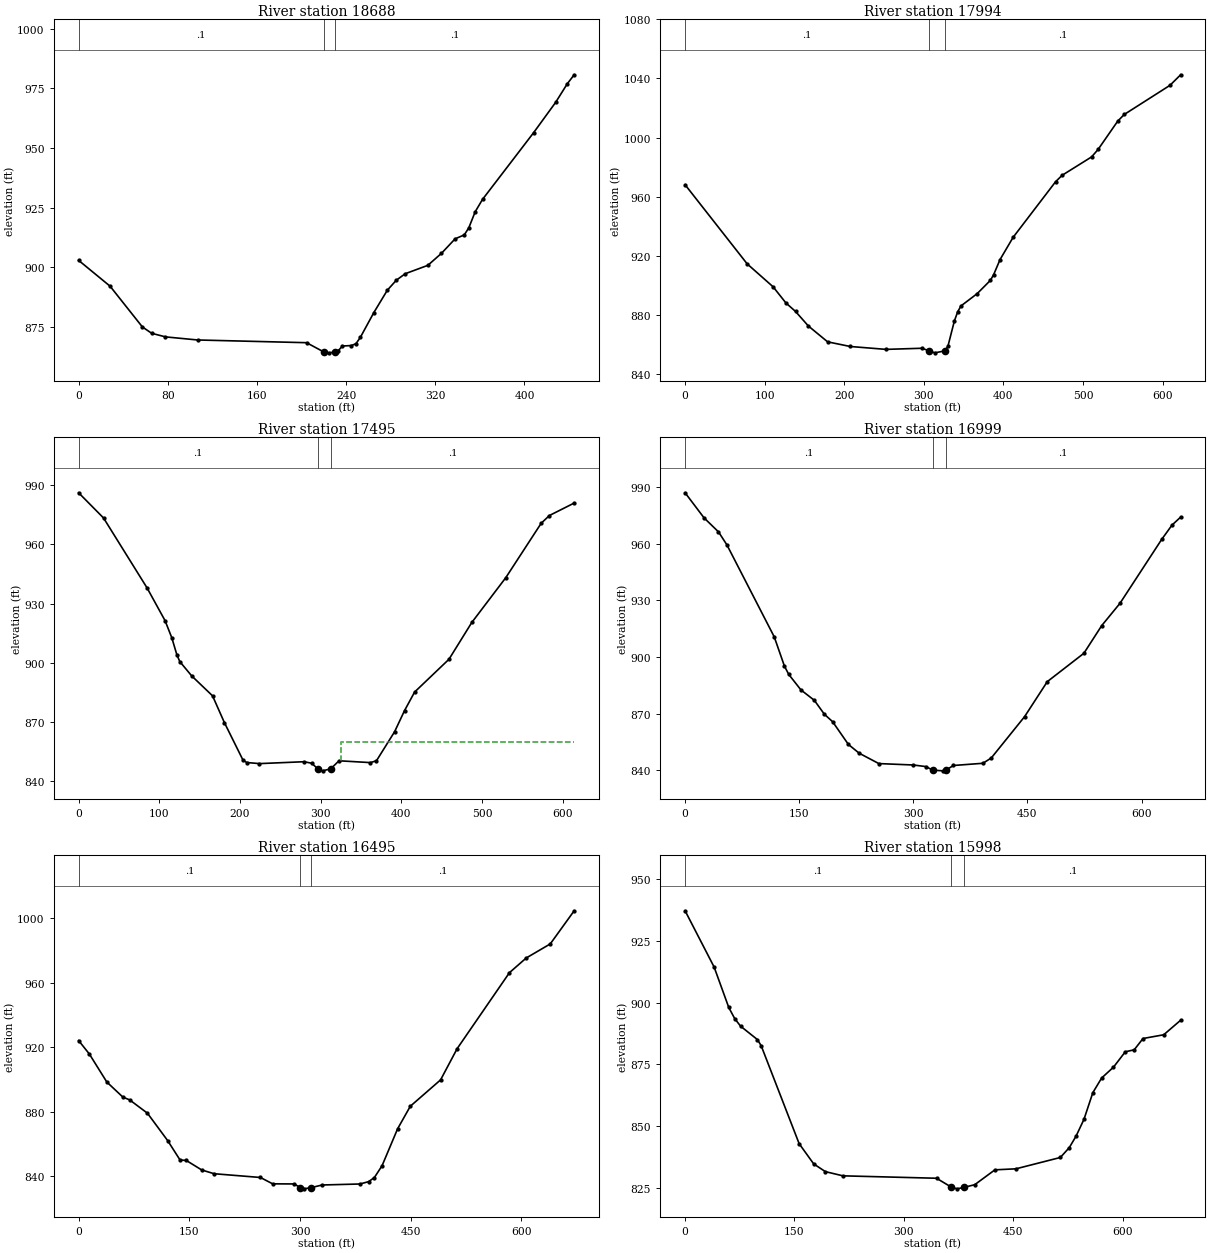
Type RM Length L Ch R = 1 ,18688   ,694.2,694.2,694.2
XS GIS Cut Line= 5
1610925.00458869380297.1942895241610957.64436343380422.454430591
1611142.47382839380445.1847361591611189.95604888380434.715545365
1611270.26766521380433.876494559
#Sta/Elev= 30
       0  902.81    28.2  891.97    57.2  874.85    65.5   872.2    77.9  870.68
   106.8  869.38   204.5  868.24   219.7  864.42   224.6  863.98   230.4  864.36
   232.7  864.78   236.7  866.83   244.8  867.06   248.8  867.81   252.8  870.51
   264.9  880.92     277   890.3   285.1  894.51   293.1  897.22   313.3  900.72
   325.5  905.75   337.8  911.87     346   913.5   350.1  916.52   355.8  923.23
   362.4  928.44   408.2  956.43     428  969.18   438.4  976.96   444.6  980.75
#Mann= 3 ,-1,0
       0      .1       0   219.7    .045       0   230.4      .1       0
Bank Sta=219.7,230.4
XS Rating Curve= 0 ,0
Exp/Cntr(USF)=0,0
Exp/Cntr=0.3,0.1

Type RM Length L Ch R = 1 ,17994   ,499,499,499
XS GIS Cut Line= 6
1610927.83181818380981.8384000961611027.79815367380960.339427337
1611116.19627084380970.9210990821611189.97827551 380985.69862859
 1611287.6398256 381007.317023681611537.12325051381065.331671417
#Sta/Elev= 30
       0  968.16      78  914.69   110.6  899.19   126.7  888.28   138.8  882.52
   154.9  872.71   179.1     862   207.5  858.86   252.4  856.91   297.4  857.66
   307.1855.9125   313.8  854.57   326.1  855.86   330.2  858.88   338.4  876.16
   342.5  882.23   346.6  886.24     367  894.56   383.5  903.47   387.6  907.24
   395.8  917.63   412.2  932.64   465.6  970.23   473.8  974.55   510.8  986.97
     519  992.03   543.6 1011.11   551.8 1015.63   609.3 1035.34   622.7 1042.47
#Mann= 3 ,-1,0
       0      .1       0   307.1    .045       0   326.1      .1       0
Bank Sta=307.1,326.1
XS Rating Curve= 0 ,0
Exp/Cntr(USF)=0,0
Exp/Cntr=0.3,0.1

Type RM Length L Ch R = 1 ,17495   ,496,496,496
XS GIS Cut Line= 6
 1611021.5494785381626.1957071721611109.69169067381590.403455928
1611186.31194426381547.8720449211611397.87090434381414.669883505
1611471.91471951381368.0462890861611555.29873909381324.678265587
#Sta/Elev= 30
       0   986.1    30.9  973.33    84.8  937.97   107.1  921.41   115.5  912.72
   121.8  904.07   125.4  900.67   140.2   893.4     166  883.33   180.7  869.77
   203.8  850.75   208.5  849.57   224.2  849.02   279.4  849.97   288.9  849.21
   296.7   846.3   302.5  845.36   312.5  846.38   322.8  850.45   361.7  849.53
   369.2  850.46   391.7  865.16     404  875.84   416.5  885.24   459.1  901.84
   487.4  920.46   529.5  943.12   573.4  970.66   583.6  974.59   614.3   980.9
#Mann= 3 ,-1,0
       0      .1       0   296.7    .045       0   312.5      .1       0
#XS Ineff= 2 , 0
                             325             860
Permanent Ineff=
       F       F
Bank Sta=296.7,312.5
XS Rating Curve= 0 ,0
Exp/Cntr(USF)=0,0
Exp/Cntr=0.3,0.1

Type RM Length L Ch R = 1 ,16999   ,503.8,503.8,503.8
XS GIS Cut Line= 6
1611265.48403001382084.3548958451611358.72039209382034.127634093
1611443.47776851381978.1451345091611503.44746484381917.346371591
1611618.96626267381680.8189575081611675.94941643381604.610776588
#Sta/Elev= 30
       0  987.12    24.9  973.82    43.9  966.38      55  959.46   117.2  910.68
   130.6  895.15   136.3  890.76   152.3  882.54   169.9  877.03   183.1  869.64
   193.9   865.7   214.7  853.61   228.9  848.96   254.7  843.48   299.9  842.73
   316.5  841.89   325.6  839.99   339.2  839.63   342.4  839.94   352.8  842.47
   391.5  843.64   402.5  846.46   446.3  868.39   476.1  886.94   524.2  901.98
   547.7  916.69   571.6  928.45   626.5   962.4   640.1     970   651.4  974.21
#Mann= 3 ,-1,0
       0      .1       0   325.6    .045       0   342.4      .1       0
Bank Sta=325.6,342.4
XS Rating Curve= 0 ,0
Exp/Cntr(USF)=0,0
Exp/Cntr=0.3,0.1

Type RM Length L Ch R = 1 ,16495   ,497.8,497.8,497.8
XS GIS Cut Line= 6
 1611581.4814295382538.2368620931611643.04265809382462.233077094
1611722.26723717382205.0442870111611757.68481725382126.384339333
1611833.88742076382051.0393456671611921.72156267381983.163825259
#Sta/Elev= 30
       0  924.05    14.5   915.7    38.2   898.3      60  888.92    69.1  887.22
    93.2  878.96   120.6  861.95   137.4   849.9   145.8  849.62   166.8   843.7
   183.6  841.37   246.3  839.04   262.9  835.09   292.2  835.03   300.6  832.63
   304.8  831.99   314.3  832.65   329.9  834.38   381.2     835   392.9  836.45
   400.7     839   411.1  846.33   432.2  869.29   449.4  883.27   490.4  899.63
   512.8  918.99   583.7  966.19   606.5  975.32     639  984.03   671.4 1004.61
#Mann= 3 ,-1,0
       0      .1       0   300.6    .045       0   314.3      .1       0
Bank Sta=300.6,314.3
XS Rating Curve= 0 ,0
Exp/Cntr(USF)=0,0
Exp/Cntr=0.3,0.1

Type RM Length L Ch R = 1 ,15998   ,502,502,502
XS GIS Cut Line= 6
1611636.63026933382599.7075396781611753.34000967382585.174760342
1611864.32535201382586.6304660891611958.34255242382593.605845839
1612058.07922959382581.2905817631612311.02491793382540.273603424
#Sta/Elev= 30
       0  937.24    39.8  914.45    59.9  898.06      68  893.58    76.1  890.49
    99.2  885.06   104.3   882.6   156.4   842.9   176.4  834.69   192.4  831.57
   216.4  829.87   344.8  828.89     365  825.31     373   824.6   382.8  825.23
   397.2  826.27   424.9   832.3   453.7  832.71   514.6   837.3   526.9   841.3
   536.2  845.96     547  852.74   559.2  863.57   571.3  869.51   587.5  873.89
   603.7  880.12   615.9  880.92     628   885.5   656.4  887.01   679.6   892.9
#Mann= 3 ,-1,0
       0      .1       0     365    .045       0   382.8      .1       0
Bank Sta=365,382.8
XS Rating Curve= 0 ,0
Exp/Cntr(USF)=0,0
Exp/Cntr=0.3,0.1

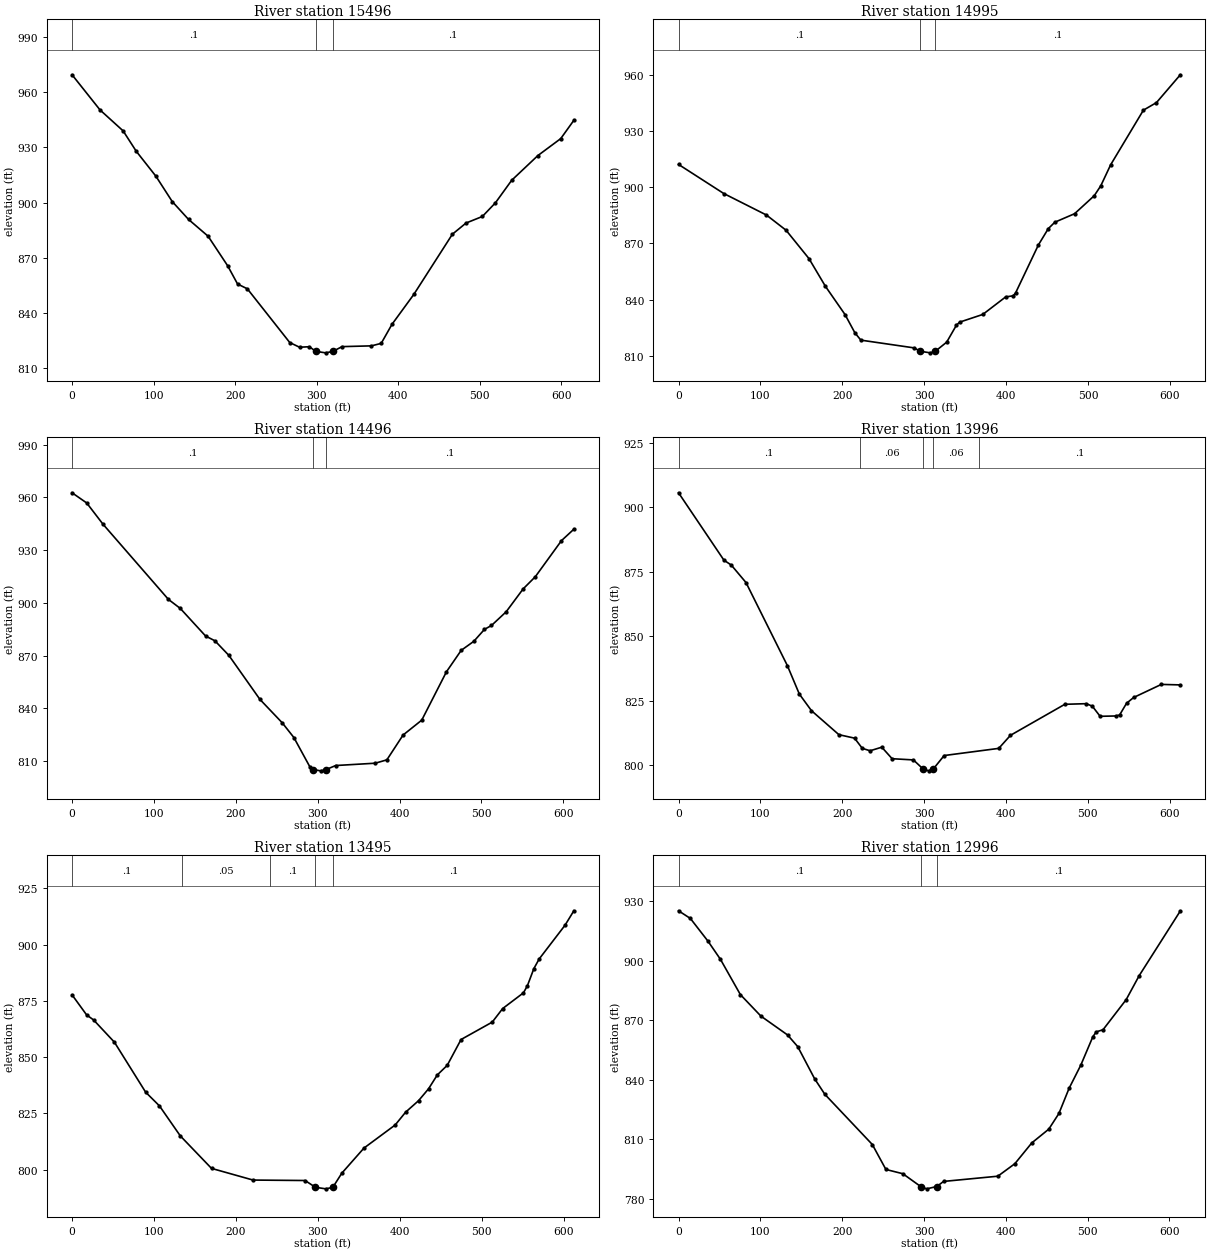
Type RM Length L Ch R = 1 ,15496   ,500.1,500.1,500.1
XS GIS Cut Line= 6
1611690.04289217383024.5964536671611784.24611583383012.788406417
1612046.58975126383003.6604719161612121.61814451383002.906864509
1612209.37026559 383005.413093091612304.19684759383001.512510344
#Sta/Elev= 30
       0  969.58    34.3  950.43    62.6  939.03    78.7  927.93   102.8  914.34
   122.8  900.56   142.8  890.82   166.8  881.67   190.8  865.55   202.9  855.66
   214.9  853.04   266.9  823.78   278.9  821.23   290.9  821.51   298.9  818.97
   310.9  818.18   319.6  818.94     331  821.56     367  821.98     379  823.33
   392.2  833.69     419     850   466.3  882.78     483  888.85     503  892.42
     519  899.84     539  912.14   571.1   925.6   599.1  934.82   615.2  944.79
#Mann= 3 ,-1,0
       0      .1       0   298.9    .045       0   319.6      .1       0
Bank Sta=298.9,319.6
XS Rating Curve= 0 ,0
Exp/Cntr(USF)=0,0
Exp/Cntr=0.3,0.1

Type RM Length L Ch R = 1 ,14995   ,499.8,499.8,499.8
XS GIS Cut Line= 6
1611664.92844109383472.6336153451611758.60738759383476.282886252
1611920.98403133383482.6086610111612020.90837218383486.501041666
  1612183.285344383492.8271445041612277.24152093383492.646042511
#Sta/Elev= 30
       0  912.13    55.2  896.61   107.3  885.13   131.3  877.01   159.3  861.86
   179.3  847.12   203.3  832.01   215.3   822.3   222.6  818.37   287.4  814.25
   295.4  812.41   307.4  811.59   313.5  812.42   327.4  817.28   339.4  826.41
   343.4  827.99   371.5  832.08   399.5  841.45   408.6  842.01   411.5  843.51
   439.5  869.24   451.5  877.87   459.5   881.3   483.6  885.83   507.6  895.43
   515.6  900.74   527.6  911.91   567.6  941.07   583.6  945.13   612.7  959.96
#Mann= 3 ,-1,0
       0      .1       0   295.4    .045       0   313.5      .1       0
Bank Sta=295.4,313.5
XS Rating Curve= 0 ,0
Exp/Cntr(USF)=0,0
Exp/Cntr=0.3,0.1

Type RM Length L Ch R = 1 ,14496   ,499.9,499.9,499.9
XS GIS Cut Line= 6
 1611946.2799125384116.4075902551612019.07373017384056.955281332
1612085.66283584384000.0265894231612142.12368092383950.625769585
1612218.79314701383886.423798248  1612415.651021383722.378194585
#Sta/Elev= 30
       0   962.6    17.9   956.8    37.7  944.77   117.7  901.95   132.2  896.81
   163.1  881.12   174.5   878.4   191.5  870.12   229.4  845.11   256.7  831.76
   270.9   823.4   290.5  806.68   294.7805.1605   303.5  804.44   309.7  805.06
     322  807.46   370.3  808.78   384.5  810.69   404.3   824.8   427.1  833.27
   457.3   860.8   475.3  872.97   490.8  878.15   503.7   884.9   512.3  887.13
   530.2   894.9     551  907.95   565.8  914.84   597.8  935.39   612.9  941.88
#Mann= 3 ,-1,0
       0      .1       0   294.7    .045       0   309.7      .1       0
Bank Sta=294.7,309.7
XS Rating Curve= 0 ,0
Exp/Cntr(USF)=0,0
Exp/Cntr=0.3,0.1

Type RM Length L Ch R = 1 ,13996   ,500.6,500.6,500.6
XS GIS Cut Line= 6
1612242.62183951384452.095895261 1612326.7122225384409.492962092
1612463.19849809384321.3008812521612547.18979992384267.029336259
1612683.67574742384178.8375835121612762.41771592384127.957435921
#Sta/Elev= 30
       0  905.66    55.5  879.48    64.4  877.61    82.4  870.82   132.9   838.6
   147.6  827.51   162.4  821.07   195.9  811.76     215  810.41   224.5  806.45
     234  805.51   248.3   806.9   260.9  802.43   286.9  801.96   298.5  798.52
   305.5  797.72   311.1   798.4   324.5  803.66   391.2  806.44   405.5  811.51
   471.9  823.55   498.1  823.79   505.5  822.82     515  818.89   534.1  819.02
   538.8  819.39   547.3  823.94     556   826.2   589.8  831.27     613  831.08
#Mann= 5 ,-1,0
       0      .1       0  221.77     .06       0   298.5    .045       0
   311.1     .06       0  366.77      .1       0
Bank Sta=298.5,311.1
XS Rating Curve= 0 ,0
Exp/Cntr(USF)=0,0
Exp/Cntr=0.3,0.1

Type RM Length L Ch R = 1 ,13495   ,499.5,499.5,499.5
XS GIS Cut Line= 6
1612211.24132484384670.6919147521612299.87041268384701.252221093
1612382.59071967 384729.776442261612453.49379309384754.225212261
1612701.65438601384839.7972195891612790.28347383384870.357854009
#Sta/Elev= 30
       0  877.67    17.8  868.75    26.3  866.52    51.7  856.64    89.8  834.44
   106.7  828.33   132.1  815.02   170.2  800.58   220.9  795.39   284.4  795.19
   297.1  792.17   309.8  791.49   318.3  792.17   329.3  798.46   356.3   809.6
   394.4  819.86   407.1  825.54   422.9  830.65   435.1  835.92   445.8  842.09
   457.9  846.35   474.8  857.83   512.9  865.57   525.6  871.59     551  878.58
   555.9  881.83   563.7  889.35   570.1  893.59   601.7   908.6   612.5  915.03
#Mann= 5 ,-1,0
       0      .1       0  133.75     .05       0  241.25      .1       0
   297.1    .045       0   318.3      .1       0
Bank Sta=297.1,318.3
XS Rating Curve= 0 ,0
Exp/Cntr(USF)=0,0
Exp/Cntr=0.3,0.1

Type RM Length L Ch R = 1 ,12996   ,500.1,500.1,500.1
XS GIS Cut Line= 6
1612065.83347918   385292.2152781612158.28703442385274.907241762
1612315.06132717385232.1510936771612411.53784026385205.839466512
1612568.31213301385163.0833184271612661.53077859385148.770026833
#Sta/Elev= 30
       0  925.19    14.5  921.31      36  909.87    51.2  900.74    75.6  882.93
   100.7  872.09   133.3  862.58   145.7  856.71   166.4  840.47   178.9  832.64
   236.9  807.35   253.5  794.78   274.2  792.63   296.2  786.12   303.3  785.01
   315.7  786.18     324  788.75   390.3  791.38   411.1  797.67   431.8  808.15
   452.6   815.1     465  823.01   477.4  835.67   491.7  847.33   506.4  861.63
   510.6  864.15   518.9  865.21   547.2  880.39   563.2  892.55   613.4  925.11
#Mann= 3 ,-1,0
       0      .1       0   296.2    .045       0   315.7      .1       0
Bank Sta=296.2,315.7
XS Rating Curve= 0 ,0
Exp/Cntr(USF)=0,0
Exp/Cntr=0.3,0.1

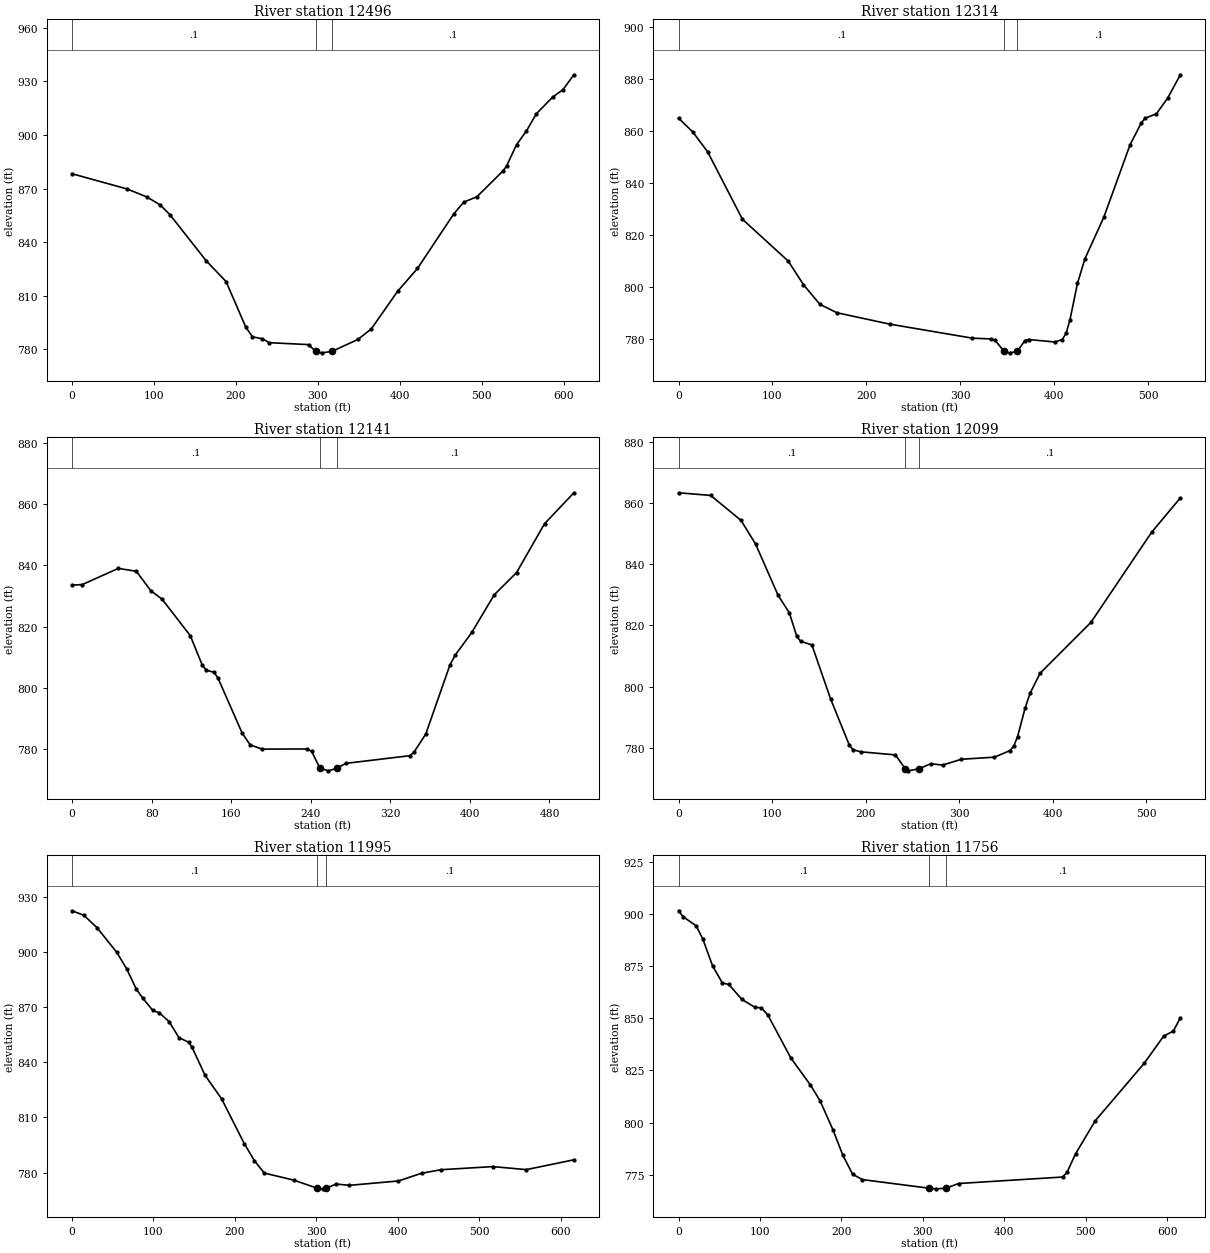
Type RM Length L Ch R = 1 ,12496   ,181.5,181.5,181.5
XS GIS Cut Line= 6
1612029.38768592385744.8118137571612283.90489343385715.062857509
1612383.22884175 385703.453300671612457.72147493 385694.74662517
1612544.56382093385684.0228933391612637.53181084385671.871342838
#Sta/Elev= 30
       0  878.28    67.2  869.77    91.3   865.3   107.5  860.86   119.5  855.34
   163.8  829.54     188  817.93   212.2  792.27   220.2  787.04   232.3  785.91
   240.7  783.75   288.7  782.65   297.4778.8394   304.8  778.05   316.9   778.8
   348.9  785.54   365.2  791.42   397.4  812.52   421.6  825.26   465.9  855.82
     478  862.36   494.1   865.4   526.4  880.05   530.4  882.67   542.5  894.51
   554.6  902.25   566.7  911.84   586.9  921.32     599  925.25   612.5  933.68
#Mann= 3 ,-1,0
       0      .1       0   297.4    .045       0   316.9      .1       0
Bank Sta=297.4,316.9
XS Rating Curve= 0 ,0
Exp/Cntr(USF)=0,0
Exp/Cntr=0.3,0.1

Type RM Length L Ch R = 1 ,12314   ,172.9,172.9,172.9
BEGIN DESCRIPTION:
Structure 3 XS 4
END DESCRIPTION:
XS GIS Cut Line= 3
1612048.33978678385772.8153036531612145.94388539385887.247695128
1612529.62896269385891.735239892
#Sta/Elev= 30
       0  865.09    15.4  859.65    30.9  852.16      68  826.21   116.8  810.11
     133  801.05   150.4  793.51   168.6  790.26   224.6   785.9   312.6   780.5
   332.6   780.2   336.6  779.76   346.8 775.366   352.6  774.85   360.6  775.38
   368.6  779.56   372.6  779.97   400.6  779.02   408.6  779.97   412.6  782.51
   416.6  787.47   424.6  801.52   432.6  811.06   452.6  826.92   480.6  854.83
   492.6  863.28   496.6  865.04   508.6  866.73   520.6  872.76   534.1  881.74
#Mann= 3 ,-1,0
       0      .1       0   346.8    .045       0   360.6      .1       0
Bank Sta=346.8,360.6
XS Rating Curve= 0 ,0
Exp/Cntr(USF)=0,0
Exp/Cntr=0.3,0.1

Type RM Length L Ch R = 1 ,12141   ,42.5,42.5,42.5
BEGIN DESCRIPTION:
Structure 3 XS 3
END DESCRIPTION:
XS GIS Cut Line= 5
 1612033.7552663386012.8989485121612249.15741496386031.971013758
 1612317.5924726386056.6525099591612408.46525407386060.018168532
1612497.09426315385972.511045639
#Sta/Elev= 30
       0  833.55    10.4  833.77    46.5  839.04    64.6   838.1    79.3  831.69
    90.4  829.01   118.8  817.06   130.9  807.39   134.9  805.71   142.9  805.04
   146.9  803.01     171  785.14   179.1  781.28   191.1   779.9   236.4  779.94
   240.9  779.16   249.2  773.64   257.7  772.79   265.9   773.6   275.2  775.23
   339.6  777.75   343.6  778.81   355.6  784.83   379.9  807.42   385.1  810.61
   401.9  818.09   424.4  830.38   446.9  837.68     475  853.65   504.5  863.79
#Mann= 3 ,-1,0
       0      .1       0   249.2    .045       0   265.9      .1       0
Bank Sta=249.2,265.9
XS Rating Curve= 0 ,0
Exp/Cntr(USF)=0,0
Exp/Cntr=0.3,0.1

Type RM Length L Ch R = 1 ,12099   ,103.3,103.3,103.3
BEGIN DESCRIPTION:
Structure 3 XS 2
END DESCRIPTION:
XS GIS Cut Line= 5
1612025.90206296386060.018168532 1612231.2072359386072.358916632
1612306.37361069386095.9185266421612415.19657122386090.309095687
1612515.04444221385988.217452312
#Sta/Elev= 30
       0  863.42    34.3  862.56    66.8  854.38    82.4   846.6   106.4  829.86
   118.4  824.11   126.4   816.4   130.4  814.83   142.5  813.62   162.5  795.94
   182.5  780.82   186.5  779.33   194.6  778.64   231.8  777.63   242.1773.1472
   244.8  772.41   256.9  773.06   269.5  774.74   282.1  774.29   302.2   776.2
   337.6  776.88   354.3  779.06   358.3  780.57   362.3  783.62   370.3  792.91
   375.6  797.76   386.3  804.35   440.7  821.02   505.6  850.52   536.2  861.74
#Mann= 3 ,-1,0
       0      .1       0   242.1    .045       0   256.9      .1       0
Bank Sta=242.1,256.9
XS Rating Curve= 0 ,0
Exp/Cntr(USF)=0,0
Exp/Cntr=0.3,0.1

Type RM Length L Ch R = 1 ,11995   ,239.6,239.6,239.6
BEGIN DESCRIPTION:
Structure 3 XS 1
END DESCRIPTION:
XS GIS Cut Line= 6
1611969.70703101386199.9775700871612065.48964784386211.540539086
 1612152.4392771386201.7364248341612226.94011234386193.098646834
1612487.69319975386162.8654395941612582.40921767386168.935637429
#Sta/Elev= 30
       0  922.36    14.5   919.9    30.6  913.21    54.8  899.83    66.9  890.92
      79  879.68      87  874.74    99.1  868.21   107.2  866.87   119.2  862.09
   131.3  853.37   143.4  850.83   147.4  848.11   163.5  832.79   183.7  820.09
   211.8  795.49   223.9  786.54     236  779.74   272.2   775.9   300.4   771.6
   308.5  771.15   312.5  771.58   324.6  773.74   340.7  773.06   400.9  775.43
   429.3  779.63   453.4  781.56   516.7  783.24     558   781.6   616.4  786.93
#Mann= 3 ,-1,0
       0      .1       0   300.4    .045       0   312.5      .1       0
Bank Sta=300.4,312.5
XS Rating Curve= 0 ,0
Exp/Cntr(USF)=0,0
Exp/Cntr=0.3,0.1

Type RM Length L Ch R = 1 ,11756   ,138.2,138.2,138.2
BEGIN DESCRIPTION:
Low water crossing
END DESCRIPTION:
XS GIS Cut Line= 6
1611966.43709541386349.9366707231612218.83533721386349.274208146
1612219.49779978386391.6718130671612223.47257524386420.157703873
1612227.44735071386467.1925468321612472.55850415386463.880233947
#Sta/Elev= 30
       0  901.67     5.7  898.81    21.7  894.44    29.7   888.2    41.7  875.35
    53.7  867.07    61.7  866.29    77.7  859.17    93.7  855.33   101.7  855.06
   109.7  851.62   137.7   831.1   161.7  818.17   173.7   810.5   189.7  796.42
   201.7  784.34   213.7   775.2   225.7  772.62   307.8  768.49   315.9  768.19
     328  768.46   343.9  770.75   471.5  773.86   476.8  776.04   487.5  785.09
   511.5  800.83   571.6  828.43   595.5  841.46   607.5  843.97     616  850.28
#Mann= 3 ,-1,0
       0      .1       0   307.8    .045       0     328      .1       0
Bank Sta=307.8,328
XS Rating Curve= 0 ,0
Exp/Cntr(USF)=0,0
Exp/Cntr=0.3,0.1

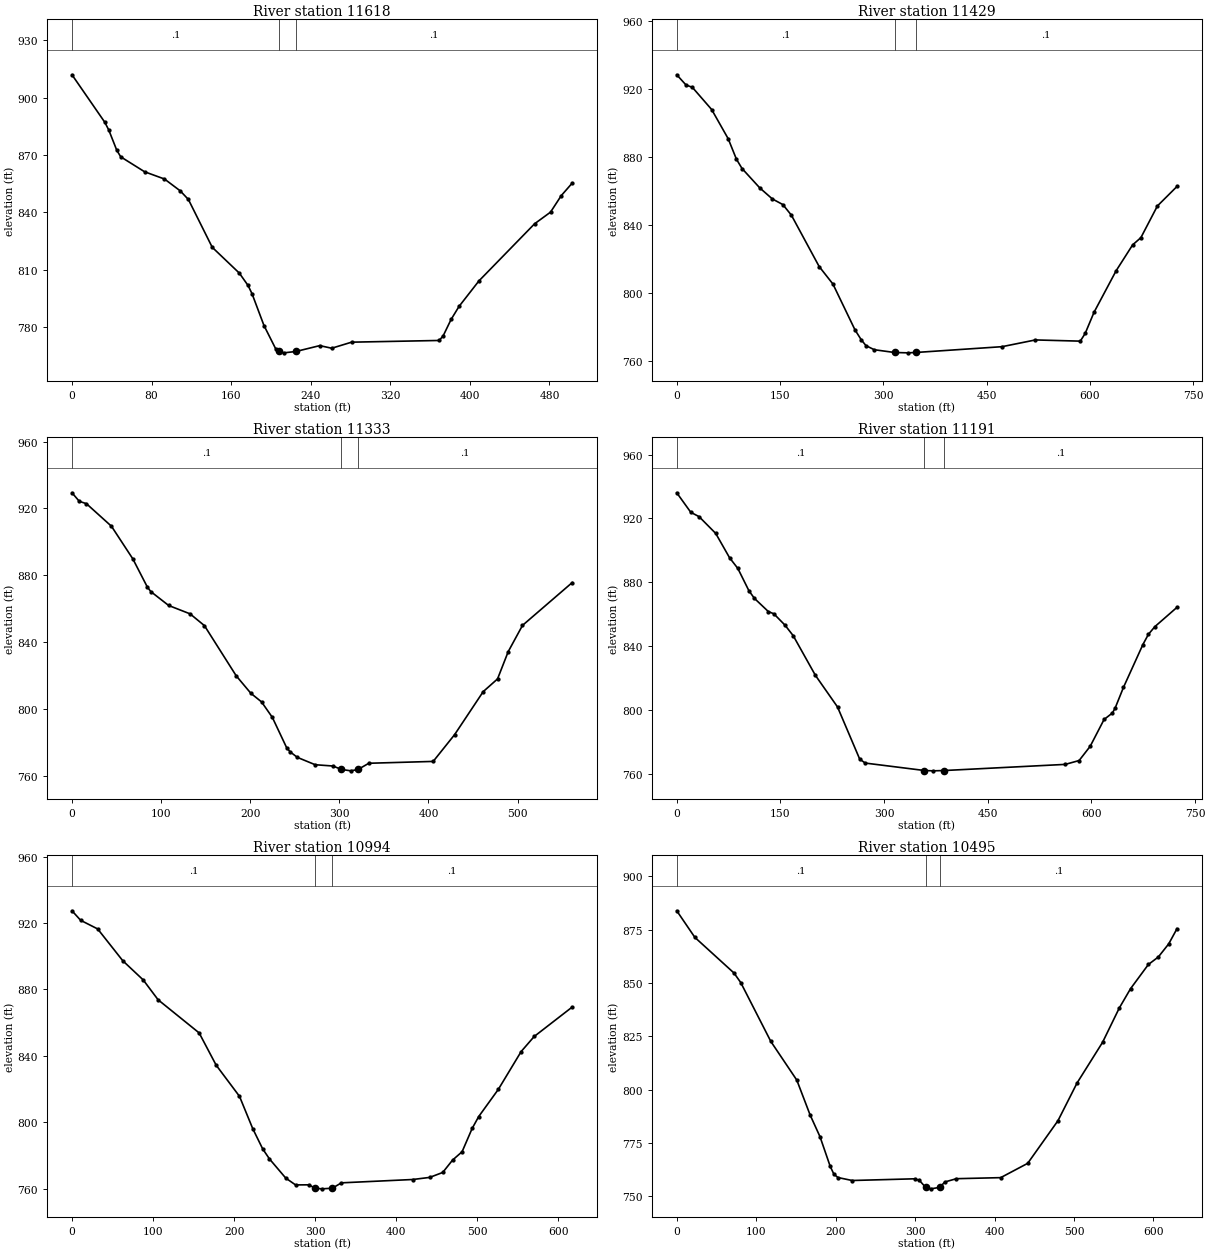
Type RM Length L Ch R = 1 ,11618   ,188.7,188.7,188.7
XS GIS Cut Line= 2
1611967.09955799386534.7637296741612469.90865385386525.489253597
#Sta/Elev= 30
       0  911.99      33  887.14      37  883.08      45  872.55      49  869.09
      73  861.27      93  857.48   108.8   851.3     117   846.8     141  821.77
   168.2  808.29     177  801.82     181   797.5     193  780.88     205  768.47
   207.8767.3363   213.1  766.59   225.1   767.3   249.1  770.36   261.1     769
   281.1  772.17   369.1  773.06   373.1  775.42   381.1  784.03   389.1  790.86
   409.1   804.2   465.1  834.09   481.1  840.17   491.9  848.82   502.9  855.36
#Mann= 3 ,-1,0
       0      .1       0   207.8    .045       0   225.1      .1       0
Bank Sta=207.8,225.1
XS Rating Curve= 0 ,0
Exp/Cntr(USF)=0,0
Exp/Cntr=0.3,0.1

Type RM Length L Ch R = 1 ,11429   ,96,96,96
BEGIN DESCRIPTION:
Low water crossing
END DESCRIPTION:
XS GIS Cut Line= 6
1611925.41382063386746.8268554511612219.10556305386756.395759339
  1612230.146606386698.9823360091612219.10556305 386639.36070409
1612226.46625835  386580.47514171612480.41024616386587.099767469
#Sta/Elev= 30
       0  928.36    13.4  922.38    22.7  920.96    50.7  907.92    74.7  890.74
    86.7  878.67    94.8  873.22   120.5  861.84   138.8  855.33   154.1     852
   166.5  845.75   206.8  815.56   226.8  805.26   258.8  778.32   267.8  772.54
   274.8  769.01   286.9  766.62   316.3 764.992   335.6  764.79   346.7  764.99
   472.3  768.41   520.8  772.38     586  771.67   593.1  776.22     606  788.69
     638  813.06     662   828.3     674  832.57     698  851.21   726.4  862.66
#Mann= 3 ,-1,0
       0      .1       0   316.3    .045       0   346.7      .1       0
Bank Sta=316.3,346.7
XS Rating Curve= 0 ,0
Exp/Cntr(USF)=0,0
Exp/Cntr=0.3,0.1

Type RM Length L Ch R = 1 ,11333   ,142.1,142.1,142.1
XS GIS Cut Line= 2
1611935.96381688386783.1871960051612495.74469434386824.922338349
#Sta/Elev= 30
       0  929.39     8.2  924.29    16.2  922.87    44.3  909.38    68.3  889.86
    84.4   873.2    88.4  870.35   108.5  862.02   132.5  857.03   148.6  849.99
   184.3  819.97   200.7  809.55   212.7   804.4   224.8  795.16   240.8  777.09
   244.8  774.55   252.9  771.24   272.9  766.85     293  766.08   302.1  764.04
     313   763.2     321  764.04   333.1  767.73   405.3  768.83   429.3  784.82
   461.4  810.53   477.5  818.14   489.5  834.48   505.5  850.13   561.3  875.73
#Mann= 3 ,-1,0
       0      .1       0   302.1    .045       0     321      .1       0
Bank Sta=302.1,321
XS Rating Curve= 0 ,0
Exp/Cntr(USF)=0,0
Exp/Cntr=0.3,0.1

Type RM Length L Ch R = 1 ,11191   ,196.6,196.6,196.6
BEGIN DESCRIPTION:
Low water crossing
END DESCRIPTION:
XS GIS Cut Line= 6
1611915.84491674386833.6830599761612207.32845057386849.876589633
1612207.32845057386899.929317664 1612200.7038248 386980.89696595
 1612200.7038248387028.0054158621612453.17567355387050.087501758
#Sta/Elev= 30
       0  936.09    20.3  923.86    32.3  921.14    56.4  910.62    76.4  895.39
    88.4  888.67   104.4  874.72   112.4  869.91   132.5  861.67   140.5  860.25
   156.5   853.2   168.5  846.54   200.6   821.7   232.6  801.88   264.7  769.21
   272.7  766.71   358.3762.0511   370.7  761.84   386.7  762.03   562.1  765.88
   582.2   768.3   598.2  777.21   618.3  794.03   630.4   798.1   634.4  801.25
   646.4  814.18   674.5     841   682.5  847.42   691.8   852.2   723.8   864.3
#Mann= 3 ,-1,0
       0      .1       0   358.3    .045       0   386.7      .1       0
Bank Sta=358.3,386.7
XS Rating Curve= 0 ,0
Exp/Cntr(USF)=0,0
Exp/Cntr=0.3,0.1

Type RM Length L Ch R = 1 ,10994   ,499.8,499.8,499.8
XS GIS Cut Line= 6
 1611847.5202675387035.9083129171611935.14771692387077.729095429
1612019.62392592387104.6722830091612093.32325359387119.747712165
1612192.32371175387133.9704527561612446.59452868387165.755494177
#Sta/Elev= 30
       0  927.34    10.7   921.6    31.7  916.41    62.7  897.26    87.9  885.72
   106.3  873.76   156.9  853.84   177.9  834.43   206.7  815.67     223  796.28
   235.3  784.06   243.7  777.99   263.8  766.46   275.9  762.36   292.1  762.42
   300.2  760.37   308.3     760   321.2 760.374   332.5  763.61   420.5  765.62
   441.4  766.88   457.5  769.86   469.6  777.28   481.4  782.34   493.8  796.34
   501.9  803.51   526.1  819.86   554.3  842.64   570.4   851.7   617.3  869.41
#Mann= 3 ,-1,0
       0      .1       0   300.2    .045       0   321.2      .1       0
Bank Sta=300.2,321.2
XS Rating Curve= 0 ,0
Exp/Cntr(USF)=0,0
Exp/Cntr=0.3,0.1

Type RM Length L Ch R = 1 ,10495   ,381.7,381.7,381.7
XS GIS Cut Line= 6
1611688.03206943387233.0381679981611743.74455643387318.624939084
1611792.06631017387398.7130335121611830.34280843387466.166966841
1611881.92439817387551.964039341   1612024.06519387765.177851751
#Sta/Elev= 30
       0  883.86    22.8  871.38      72  854.69    80.5  850.22   118.4  822.58
   151.1  804.44   167.9  788.05   180.3  777.89   193.1  764.03   197.8   760.3
   202.9  758.74   220.8  757.35   299.6  758.15   305.4  757.41   313.3  754.11
     320  753.44     331  754.15   337.4  756.66     352   758.2   407.7  758.69
   441.7   765.4   479.8   785.4   503.8  803.07   535.9  822.14     557  838.27
   571.1  847.29   593.6  858.67   606.1  862.18   619.2  868.34   629.6  875.45
#Mann= 3 ,-1,0
       0      .1       0   313.3    .045       0     331      .1       0
Bank Sta=313.3,331
XS Rating Curve= 0 ,0
Exp/Cntr(USF)=0,0
Exp/Cntr=0.3,0.1

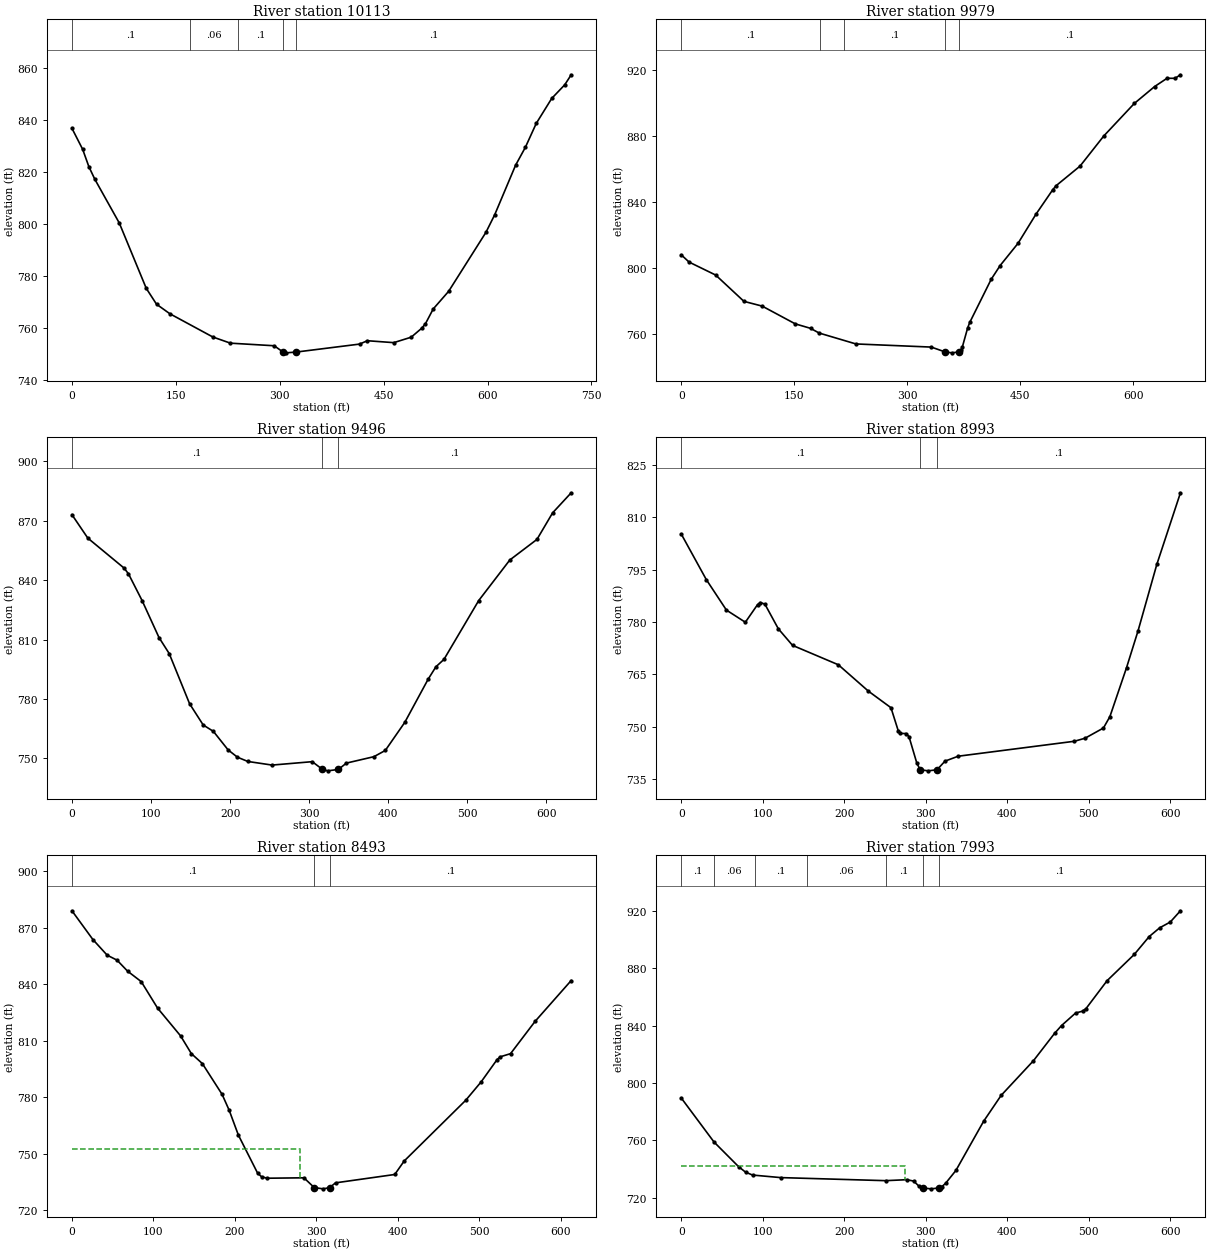
Type RM Length L Ch R = 1 ,10113   ,133.7,133.7,133.7
BEGIN DESCRIPTION:
Low water crossing
END DESCRIPTION:
XS GIS Cut Line= 6
 1611315.9482499387562.3918945491611533.08876121387732.423955949
1611581.66935018387687.5237146271611617.00068762387665.441628731
1611644.97132975387650.7202381331611837.82154658387887.734626752
#Sta/Elev= 30
       0  836.93    15.5  828.82    24.4  822.17      33  817.31    68.4   800.4
   107.3  775.23   122.1  769.12   141.3  765.45   203.4  756.48   228.8   754.1
     292   753.1   304.9750.6545     309  750.37   323.1  750.65   415.2  753.74
   426.5  755.04   464.6   754.3   489.8   756.4   505.2  759.91   510.4  761.61
   521.6  767.29   543.9   774.1   597.7  796.82   610.3  803.57   640.5  822.69
   654.7  829.64   670.3   838.8   692.7  848.46   711.5  853.71   720.8  857.57
#Mann= 5 ,-1,0
       0      .1       0     170     .06       0     240      .1       0
   304.9    .045       0   323.1      .1       0
Bank Sta=304.9,323.1
XS Rating Curve= 0 ,0
Exp/Cntr(USF)=0,0
Exp/Cntr=0.3,0.1

Type RM Length L Ch R = 1 ,9979    ,483.4,483.4,483.4
XS GIS Cut Line= 6
1611271.39281084387606.6460165831611357.28174667387665.417224512
1611442.03256142387723.4846936761611519.58686826387777.616475165
  1611590.569994387855.3656634991611708.29679267388082.971835583
#Sta/Elev= 30
       0   808.2    10.5  803.78    45.8  795.94    83.3  780.03   107.5  777.16
   151.5  766.41   171.7  763.72   183.2  760.86     232  754.27   332.1  752.37
   350.4749.4448   359.5  748.89   368.9  749.45   371.8   750.8   373.4  752.59
   380.3  763.88   383.1  767.25   411.6  793.37   423.5  801.71   447.3  815.17
     471  832.71   493.5  847.67   498.1  850.11   529.6  861.86   561.1  880.07
   601.6  899.73   628.6  909.97   645.1  914.98   655.7  914.94   662.9  917.09
#Mann= 5 ,-1,0
       0      .1       0  184.07     .06       0  216.81      .1       0
   350.4    .045       0   368.9      .1       0
Bank Sta=350.4,368.9
XS Rating Curve= 0 ,0
Exp/Cntr(USF)=0,0
Exp/Cntr=0.3,0.1

Type RM Length L Ch R = 1 ,9496    ,503.1,503.1,503.1
XS GIS Cut Line= 6
1611040.54911242387797.7247026711611075.94733559387890.196630582
1611109.96301559387977.0209320041611143.06662393 388050.62478742
1611200.23252009388135.3788830041611349.44580434388343.606812999
#Sta/Elev= 30
       0  873.09    20.1  861.24    65.9  846.12    71.5   843.2    88.7  829.72
   110.1  811.03     123  802.94   148.8  777.57     166  766.86   178.9  763.62
   197.5  754.27   209.3  750.58   222.4  748.43   253.1   746.6   303.9  748.32
   316.7744.4708   323.5  743.69     337744.4025   347.1   747.6   381.9  750.84
   396.3  753.99   420.9  768.15   450.5  789.99   460.3  796.25   470.5  799.99
   514.4  829.69   553.8  850.21   588.1   860.6   607.9  874.01   631.4  884.15
#Mann= 3 ,-1,0
       0      .1       0   316.7    .045       0     337      .1       0
Bank Sta=316.7,337
XS Rating Curve= 0 ,0
Exp/Cntr(USF)=0,0
Exp/Cntr=0.3,0.1

Type RM Length L Ch R = 1 ,8993    ,499.6,499.6,499.6
XS GIS Cut Line= 6
1610533.83490276388090.2303512541610710.63080901388275.722106263
 1610779.6247655388348.1091005951610831.63876909388402.142785177
1610894.03168893388463.5530954151610961.61357476 388528.65106234
#Sta/Elev= 30
       0  805.27    30.8  792.19    55.5  783.45    78.7  779.97    93.7  785.02
    97.1  785.62   102.7  785.16   119.2  778.09   136.6  773.35   192.8  767.79
   229.7  760.23   257.4  755.48   266.4  748.82   268.4  748.11   275.8  748.09
   279.5  747.21     289  739.71   293.2  737.71   303.1   737.4   313.9737.7068
   323.7  740.18   339.9  741.59   482.4  745.87   495.5  746.74   518.1  749.67
     526  752.92   546.4  766.92   560.6  777.53   583.6  796.54   612.6  817.06
#Mann= 3 ,-1,0
       0      .1       0   293.2    .045       0   313.9      .1       0
Bank Sta=293.2,313.9
XS Rating Curve= 0 ,0
Exp/Cntr(USF)=0,0
Exp/Cntr=0.3,0.1

Type RM Length L Ch R = 1 ,8493    ,499.5,499.5,499.5
XS GIS Cut Line= 6
1610151.72149375388506.6484816671610230.63144092388557.273708507
1610368.16036534388643.8302939241610452.79339817388697.096263513
1610590.32232259388783.6531770081610669.66566785   388833.590085
#Sta/Elev= 30
       0  878.88    25.7  863.63    43.2  855.34    55.4  852.67    68.2  846.88
      85  841.31     105  827.29   133.3  812.52   146.5  803.12     160  797.84
   184.2  781.52   192.9  773.09   204.2  759.89   227.8  739.71   232.6  737.82
   239.3  737.03   284.6  737.25   297.3  732.06   308.2   731.4     316  732.02
   323.4  734.58     396  739.01   407.6  746.16     483  778.32     502  788.12
   521.6  799.97   525.6  801.45   538.1   803.1   568.1  820.17   612.5  841.89
#Mann= 3 ,-1,0
       0      .1       0   297.3    .045       0     316      .1       0
#XS Ineff= 2 , 0
          280.21   752.6
Permanent Ineff=
       F       F
Bank Sta=297.3,316
XS Rating Curve= 0 ,0
Exp/Cntr(USF)=0,0
Exp/Cntr=0.3,0.1

Type RM Length L Ch R = 1 ,7993    ,500.3,500.3,500.3
XS GIS Cut Line= 6
1609838.66011201388956.0435802491610077.13240409389049.764849499
1610169.58333467389087.8858362591610239.25872026389115.672198012
1610320.60140534389147.9595350031610407.77741209389182.497523665
#Sta/Elev= 30
       0  789.61    40.2  758.96    70.3  741.82    78.9  737.96    87.5  735.92
   121.9  734.15   250.8  732.01   276.8  732.69   285.1  731.72   291.3  728.42
   296.2726.9073   306.6  726.32   315.7   726.9     320  727.94   324.4  730.19
     337   739.1     371  773.33   392.5  791.36   432.2  815.54     458   834.5
   466.6  839.99   483.8  848.68   492.4  850.02   496.7  851.84   522.5  871.23
   555.8  889.48   574.2  901.97   587.1  908.06     600  912.05   612.5  919.89
#Mann= 7 ,-1,0
       0      .1       0      40     .06       0      90      .1       0
  153.74     .06       0  251.23      .1       0   296.2    .045       0
   315.7      .1       0
#XS Ineff= 2 , 0
           274.9  742.42
Permanent Ineff=
       F       F
Bank Sta=296.2,315.7
XS Rating Curve= 0 ,0
Exp/Cntr(USF)=0,0
Exp/Cntr=0.3,0.1