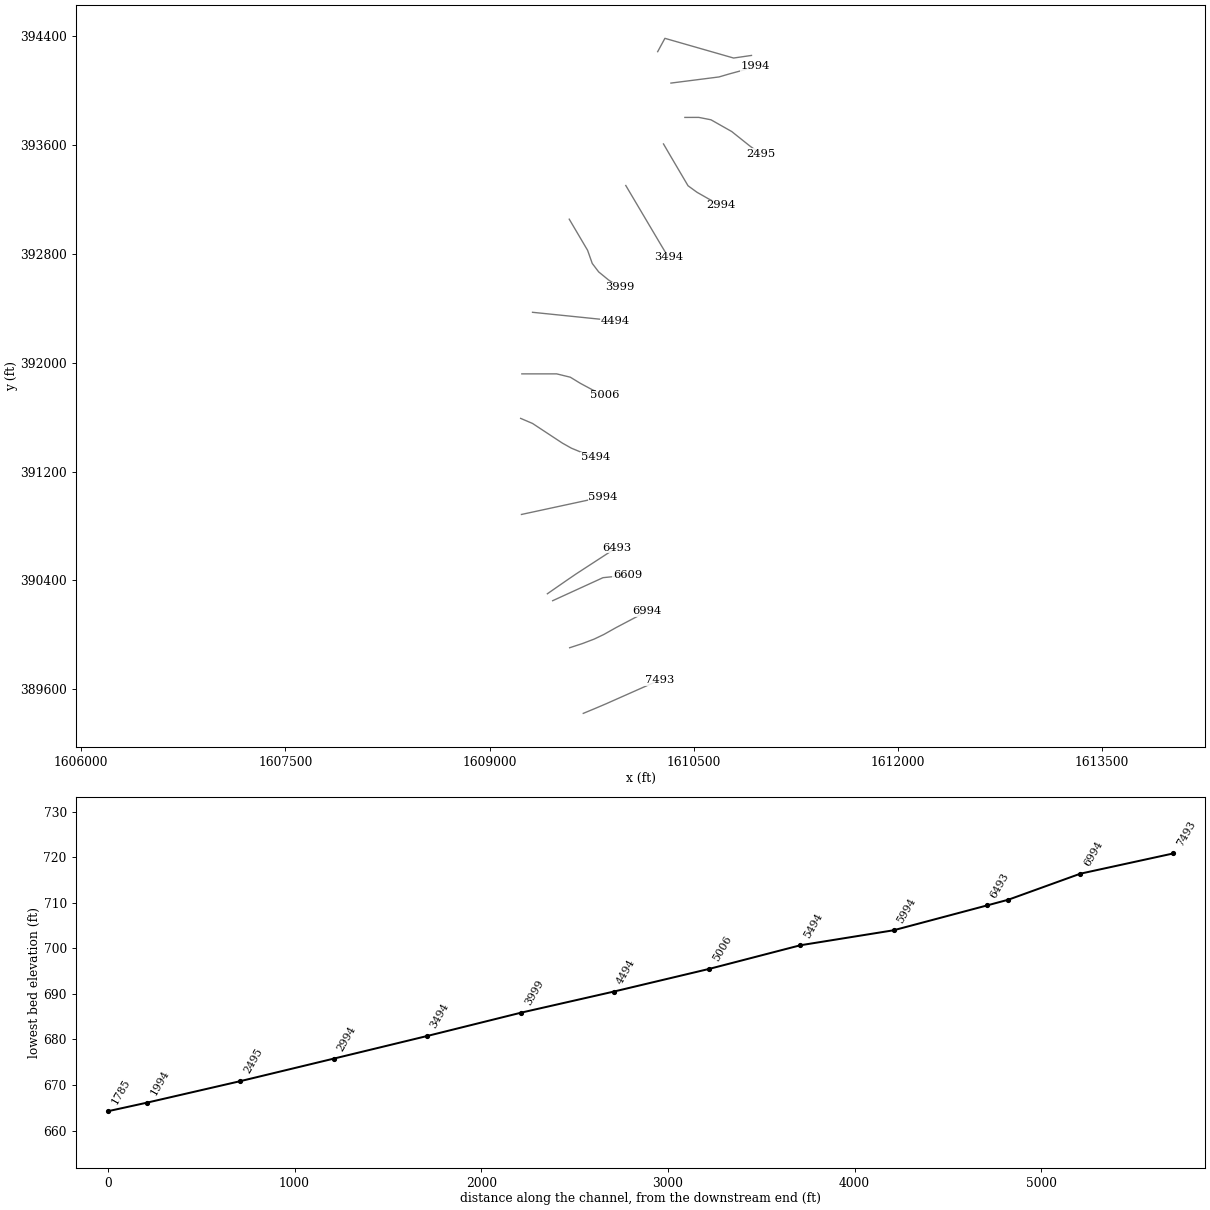
HEC-RAS study STATERN.prj: STATERN

--- STATERN.g01 (geometry) --- (continued)

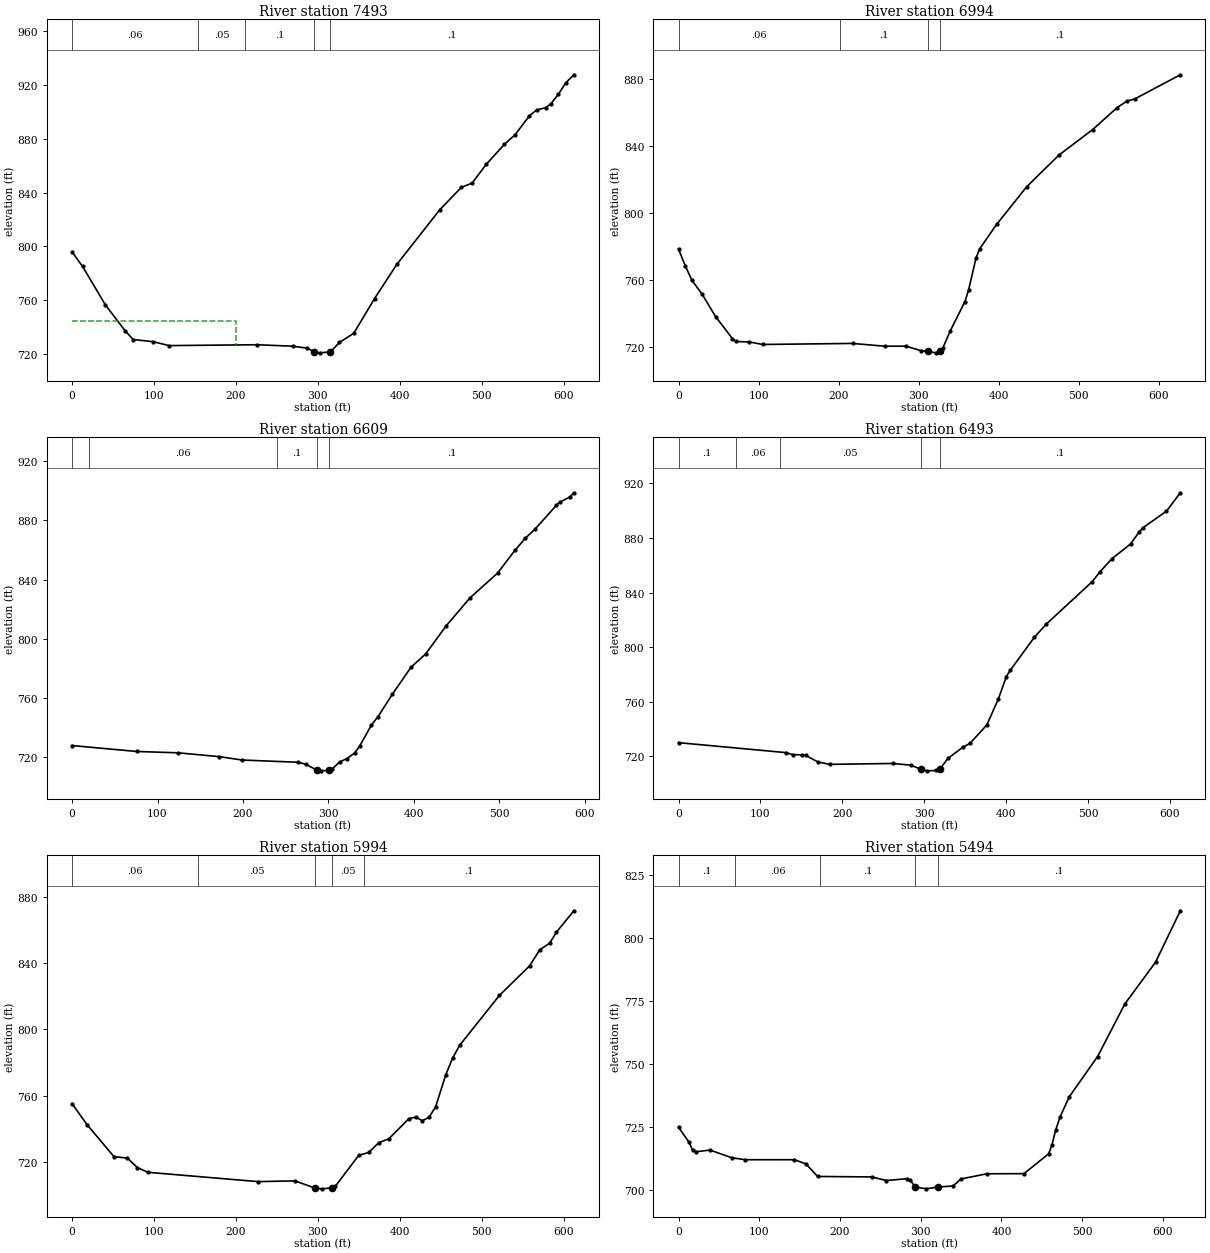
Type RM Length L Ch R = 1 ,7493    ,498.8,498.8,498.8
XS GIS Cut Line= 6
1609688.32937592389422.9448774161609774.92861217389458.924792334
1609855.44583958389493.2016266731609924.00639801  389523.6064215
1610163.96818842389630.0241876691610249.66880442389668.030017167
#Sta/Elev= 30
       0  795.85    12.8  785.06    40.8  756.33    64.7  737.29    74.5  730.72
      99  729.11   118.3  726.19   225.8  726.82   269.5  725.75     287  724.28
   295.8  721.52   302.5  720.81   315.4 721.541   326.4  728.55   343.9  735.38
   369.2  761.14   396.4  786.58   448.9  827.24   475.2  843.83   488.3     847
   505.6  861.01   527.7  875.77   540.8  882.98   558.3  897.02   567.1  901.36
   578.4  903.13   584.6  906.04   593.6  913.02   602.6  921.55   612.5  927.52
#Mann= 5 ,-1,0
       0     .06       0  153.78     .05       0  211.29      .1       0
   295.8    .045       0   315.4      .1       0
#XS Ineff= 2 , 0
          199.99  744.39
Permanent Ineff=
       F       F
Bank Sta=295.8,315.4
XS Rating Curve= 0 ,0
Exp/Cntr(USF)=0,0
Exp/Cntr=0.3,0.1

Type RM Length L Ch R = 1 ,6994    ,385.8,385.8,385.8
XS GIS Cut Line= 6
1609588.24525851389905.154542923 1609682.0679055389935.891358092
1609768.58807367389968.8276439161609839.81857425390002.860384256
1609927.26984292390052.0600890071610153.87831359390171.587409005
#Sta/Elev= 30
       0  778.38     8.3  768.43    16.7  759.71    29.3   751.5    46.2  738.04
    67.2  724.92    71.4  723.14    88.3  722.87   105.2  721.36   217.4  721.98
   257.3  720.33   284.4  720.33   302.7  717.66   311.9  717.28   321.1  716.36
   326.7717.2467   330.3   719.4   339.4  729.46   357.8  747.02   362.4  754.07
   371.5  772.83   376.1  778.46   397.3  793.05   434.9  815.58   475.2  834.49
   517.4  849.75   547.9  862.87   560.2  866.73   569.9  868.02   626.8  882.44
#Mann= 4 ,-1,0
       0     .06       0  201.31      .1       0   311.9    .045       0
   326.7      .1       0
Bank Sta=311.9,326.7
XS Rating Curve= 0 ,0
Exp/Cntr(USF)=0,0
Exp/Cntr=0.3,0.1

Type RM Length L Ch R = 1 ,6609    ,115.3,115.3,115.3
XS GIS Cut Line= 3
1609463.37153622390250.7363524721609833.16937495390419.945014123
1610012.83820841390438.404140849
#Sta/Elev= 30
       0  727.75    75.6  723.74     124  722.84   172.4  720.25   198.8  717.97
   264.7  716.44   273.6  715.08   286.7  711.08   291.1  710.65   300.7  711.02
   304.3  711.82   313.1  716.64   321.8  718.96   330.7  722.69   336.9  727.67
   350.4   741.6     358  747.22   374.7  762.27   396.7  780.71   413.7  789.61
   437.8  808.65   465.9  827.68   498.1  844.41   518.2  859.65   530.3  867.78
   542.3  874.34   566.7  890.09   570.6  892.27   582.5  895.75   587.3  898.66
#Mann= 5 ,-1,0
       0      .1       0      20     .06       0     240      .1       0
   286.7    .045       0   300.7      .1       0
Bank Sta=286.7,300.7
XS Rating Curve= 0 ,0
Exp/Cntr(USF)=0,0
Exp/Cntr=0.3,0.1

Type RM Length L Ch R = 1 ,6493    ,499.6,499.6,499.6
XS GIS Cut Line= 6
 1609424.5805596390301.7429885861609501.57909326390355.305873588
1609573.56156084390405.1174537541609635.51222435390447.426752344
1609719.32078376390501.9804490061609934.17173201390641.634041086
#Sta/Elev= 30
       0  730.03   130.9  722.75   139.6  721.23   151.1  721.15   155.3  720.69
   169.8  715.98   184.4  714.14   261.8  714.78   283.6  713.54   295.6  710.58
   303.8  709.38   314.3  709.63   319.1  710.67   328.7  718.43   347.2  726.72
   355.9  729.56   376.4  743.05   390.6  762.27   400.2  778.49     405  783.07
   434.4  807.28   449.1  816.99   505.2  848.13   514.7  855.38     529  864.81
   551.9  875.67   562.4  884.49   567.2  887.66   595.7   899.7   612.6  913.17
#Mann= 5 ,-1,0
       0      .1       0      70     .06       0   123.8     .05       0
   295.6    .045       0   319.1      .1       0
Bank Sta=295.6,319.1
XS Rating Curve= 0 ,0
Exp/Cntr(USF)=0,0
Exp/Cntr=0.3,0.1

Type RM Length L Ch R = 1 ,5994    ,499.5,499.5,499.5
XS GIS Cut Line= 6
1609234.16197717390884.4767312561609325.80647892390904.232925341
1609411.34174092390922.6715367591609484.65753917390938.476295173
1609582.41193683390959.5490876731609832.90782693391013.548651591
#Sta/Elev= 30
       0  755.26    18.4  742.54    51.1  723.36    67.5  722.47    79.7  716.74
    92.6   713.9   227.1  708.29   272.1  708.73   296.6  704.39   304.8  703.94
   317.1  704.52   321.2  705.38   349.8  724.09   362.1  725.88   374.4  731.76
   386.6  734.06   411.2  746.24   419.4  747.16   427.6     745   435.7  747.03
   443.9  753.51   456.1  772.61   464.4  782.58     473  790.37   521.7  820.52
   558.5  838.28   570.8  847.96     583  851.98   591.2  858.59   612.5  871.48
#Mann= 5 ,-1,0
       0     .06       0  153.75     .05       0   296.6    .045       0
   317.1     .05       0  356.25      .1       0
Bank Sta=296.6,317.1
XS Rating Curve= 0 ,0
Exp/Cntr(USF)=0,0
Exp/Cntr=0.3,0.1

Type RM Length L Ch R = 1 ,5494    ,487.8,487.8,487.8
XS GIS Cut Line= 6
1609228.17675292 391590.355896921609315.59193243391553.048228756
1609534.82246509391408.6728613381609600.87876342391371.505940929
1609684.61448833391336.9157870111609777.28359434391306.093670174
#Sta/Elev= 30
       0  725.04      13  719.09    17.3  716.02    21.7  715.35    39.1  715.99
    65.8  712.98    82.6  712.17   143.6  712.18   157.9  710.51   172.3  705.55
   239.4  705.36   257.5  703.95   282.5  704.65   287.2  704.05   293.1 701.377
   306.9  700.65   320.8  701.36   339.9  701.78   349.9  704.56     382  706.62
   427.9  706.66   458.5  714.54   462.6  718.07   467.1   723.8   472.5  729.05
     484  737.08   519.1  753.04   552.9  773.86   590.9   790.4   621.6  810.74
#Mann= 5 ,-1,0
       0      .1       0      70     .06       0  175.04      .1       0
   293.1    .045       0   320.8      .1       0
Bank Sta=293.1,320.8
XS Rating Curve= 0 ,0
Exp/Cntr(USF)=0,0
Exp/Cntr=0.3,0.1

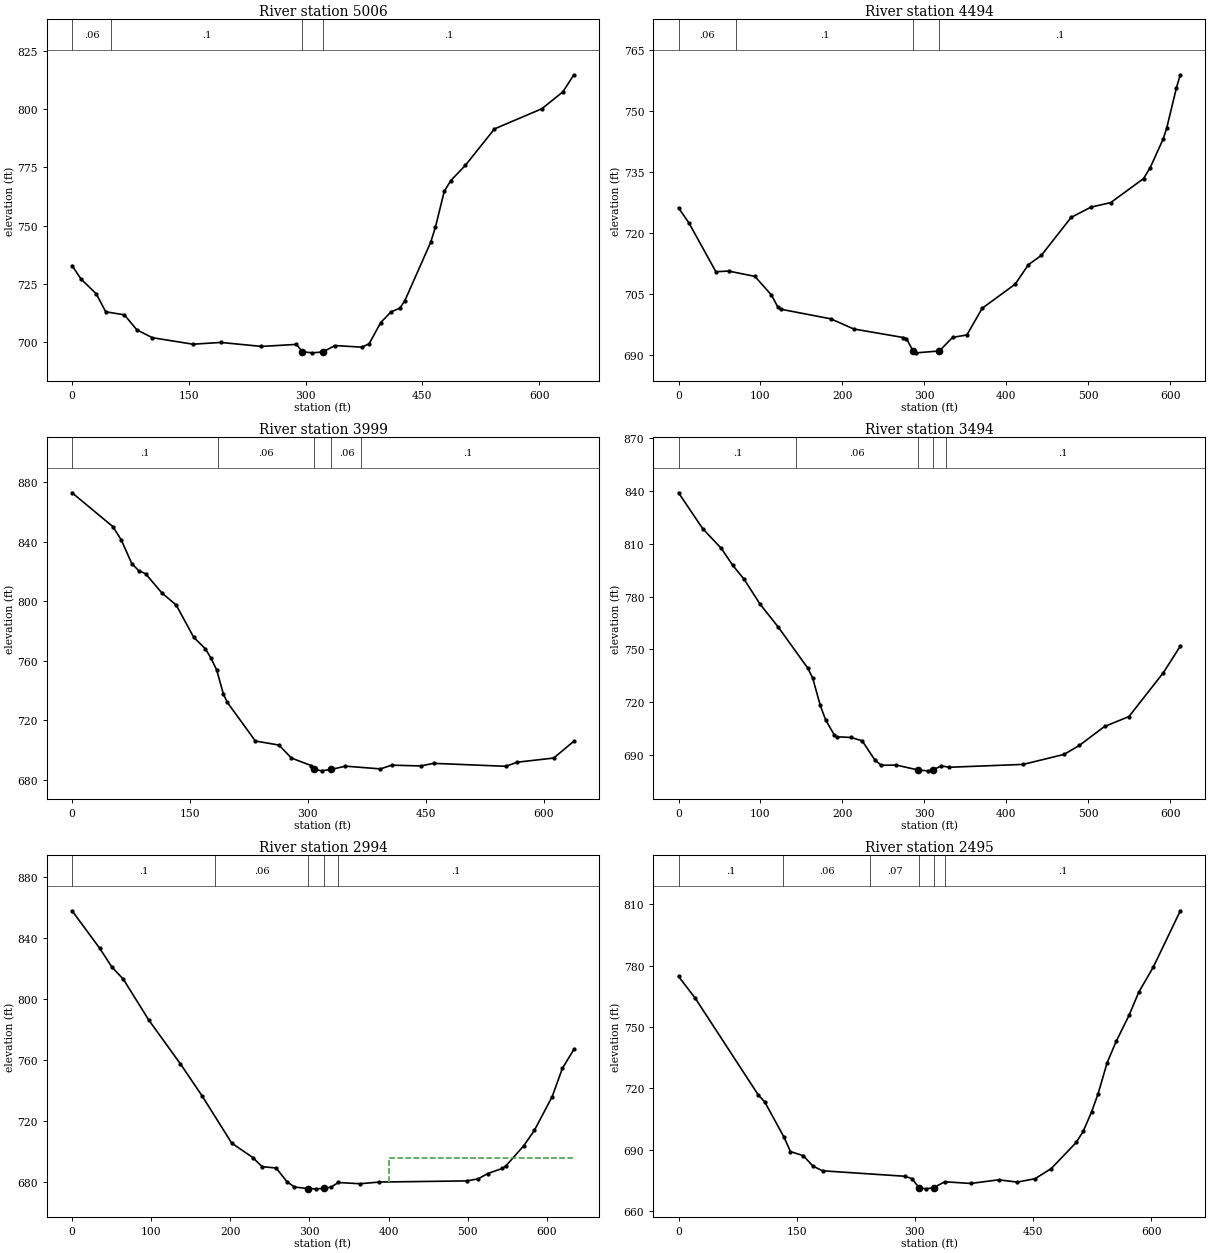
Type RM Length L Ch R = 1 ,5006    ,512.4,512.4,512.4
XS GIS Cut Line= 6
1609236.90245725391917.4218438421609493.15260093391917.421843842
  1609593.152729391892.8818666791609666.28709717391848.161155596
1609752.25214835391802.0004867611609844.87794735391759.325703338
#Sta/Elev= 30
       0  732.86    11.2  727.23    31.2   720.7    43.2  713.06    67.2  711.76
    83.2  705.32   103.2  701.96   155.2  699.17   191.2  699.93   243.2  698.22
   288.1  699.09   295.8  695.93   308.7  695.47   322.3  695.88   337.6  698.59
   372.1  697.91   381.4  699.29   396.5  708.46   409.6  713.02   421.2  714.65
   427.5  717.89   460.6  742.86   466.7  749.35     478  764.67   486.4  769.29
   505.1  775.81   542.5  791.44   603.4  800.09   630.4  807.34   644.5  814.65
#Mann= 4 ,-1,0
       0     .06       0      50      .1       0   295.8    .045       0
   322.3      .1       0
Bank Sta=295.8,322.3
XS Rating Curve= 0 ,0
Exp/Cntr(USF)=0,0
Exp/Cntr=0.3,0.1

Type RM Length L Ch R = 1 ,4494    ,494.8,494.8,494.8
XS GIS Cut Line= 6
1609315.38228717392369.8254665881609408.64489593 392360.27824159
1609570.30008443392343.7310305831609669.78020042392333.547980085
  1609831.435717392317.0007690941609924.78067468392308.260957167
#Sta/Elev= 30
       0  726.12    12.8  722.38    45.6  710.42      61  710.59    93.2  709.28
   113.3  704.72   121.4  701.68   125.4  701.18   185.7  698.85   213.8  696.35
   274.2  694.25   278.2  693.99   286.2  690.95   290.2  690.48   318.4  690.94
   334.5  694.28     352  694.88   370.7  701.45   410.9  707.36     427  712.14
   442.8  714.44   479.2  723.77   503.3   726.3   527.5  727.42   567.6  733.32
   575.7     736   591.7  743.13   595.8  745.67   607.8   755.7   612.5  758.85
#Mann= 4 ,-1,0
       0     .06       0      70      .1       0   286.2    .045       0
   318.4      .1       0
Bank Sta=286.2,318.4
XS Rating Curve= 0 ,0
Exp/Cntr(USF)=0,0
Exp/Cntr=0.3,0.1

Type RM Length L Ch R = 1 ,3999    ,505.2,505.2,505.2
XS GIS Cut Line= 6
1609585.17275809393054.0081533341609720.14886609392825.046669006
1609754.21474284392728.7843943391609801.46727301 392666.62408559
1609873.19449176392607.9204628321609956.79832718392553.722408503
#Sta/Elev= 30
       0   872.8    52.1  849.97    62.5  841.15      76  825.17    84.8  820.45
    93.5   818.4   114.1  805.54   132.4  797.37   154.8  775.63   169.7  767.85
   176.7  761.62     184  753.64   192.6  737.29   197.5  731.88   233.2  705.92
   263.2  703.19   279.1  694.45   304.5  689.35   308.1686.8974   317.3  685.87
     330  686.84   347.7  689.01   392.3  687.18   406.6  689.69   443.7  689.16
   459.8  690.91   551.7  688.92   566.4  691.68   612.7  694.48   638.3  705.79
#Mann= 5 ,-1,0
       0      .1       0  185.93     .06       0   308.1    .045       0
     330     .06       0  367.92      .1       0
Bank Sta=308.1,330
XS Rating Curve= 0 ,0
Exp/Cntr(USF)=0,0
Exp/Cntr=0.3,0.1

Type RM Length L Ch R = 1 ,3494    ,500,500,500
XS GIS Cut Line= 6
1610000.60729468393301.4299025831610048.37163484393220.759788334
1610092.95192626393145.4679441751610220.32470301392930.348951846
1610264.98865567392855.1066482511610313.56500208392774.917832255
#Sta/Elev= 30
       0  839.07    29.5  818.65    52.2   807.4    66.1   797.8    80.1  789.77
    99.6  775.61   121.9  762.49     158  739.05   163.8  733.49     173  717.99
   179.6  709.68   190.1  701.19     193  700.12   210.5  699.74   224.2  697.81
   239.7  686.88   247.4  683.92     266     684   292.3681.2272   303.9  680.73
   310.5681.2505   320.9  683.59   330.2  682.76   420.7   684.4   470.6  690.09
   489.2  695.19     520  705.98   549.8  711.64   591.9  736.69   612.5  751.77
#Mann= 5 ,-1,0
       0      .1       0  143.75     .06       0   292.3    .045       0
   310.5     .06       0  326.25      .1       0
Bank Sta=292.3,310.5
XS Rating Curve= 0 ,0
Exp/Cntr(USF)=0,0
Exp/Cntr=0.3,0.1

Type RM Length L Ch R = 1 ,2994    ,499.2,499.2,499.2
XS GIS Cut Line= 6
1610277.70090058393606.7478615051610324.85533383 393525.71849601
 1610458.0191095393299.5024130051610523.69647159 393251.75578934
1610606.93843108393204.2719604221610696.33424968393157.239574179
#Sta/Elev= 30
       0  857.92      35   833.3    50.2  821.16    64.8   813.1      97  786.31
   136.9  757.68   164.2  736.78   201.8  705.73   228.5  696.26   240.2   690.3
     258  689.41   271.5  680.54   281.1  676.95   298.6  675.95   308.6  675.77
   317.9  676.06   327.2  676.85   336.6  679.93   363.8  679.11   388.5  680.22
   498.8  680.96   513.4   682.3   525.4  685.81   543.7   689.1   548.2  690.66
   570.8   703.9   584.3  713.99   606.9  736.15   619.8   754.7   634.3  767.06
#Mann= 5 ,-1,0
       0      .1       0  181.25     .06       0   298.6    .045       0
   317.9     .06       0  336.25      .1       0
#XS Ineff= 2 , 0
                          400.05          695.94
Permanent Ineff=
       F       F
Bank Sta=298.6,317.9
XS Rating Curve= 0 ,0
Exp/Cntr(USF)=0,0
Exp/Cntr=0.3,0.1

Type RM Length L Ch R = 1 ,2495    ,501.1,501.1,501.1
XS GIS Cut Line= 6
 1610434.7947465 393801.649046511610537.29946275393801.774046257
1610626.58701384393784.2363516691610778.88100059393698.011786595
1610911.48605034393592.2131136661610991.79724142393534.458307922
#Sta/Elev= 30
       0  774.76    21.3  764.05   101.3  716.75   109.4   713.4   133.9  696.13
   142.1  689.07   158.4  687.06   170.6  681.97   182.8  679.67   287.1     677
   296.3  675.86   305.5  671.36   314.6  670.84   323.9  671.44   338.2   674.3
   370.8  673.47   406.5  675.25   430.1  674.14   452.6  675.78   473.2  680.76
   504.9  693.53   513.7  698.92   524.6  708.64   532.7  717.38   544.1  732.43
   555.6  742.95   571.9  755.65   584.2  766.94     603   779.5   637.1  806.88
#Mann= 6 ,-1,0
       0      .1       0   132.5     .06       0   243.5     .07       0
   305.5    .045       0   323.9     .07       0   338.5      .1       0
Bank Sta=305.5,323.9
XS Rating Curve= 0 ,0
Exp/Cntr(USF)=0,0
Exp/Cntr=0.3,0.1

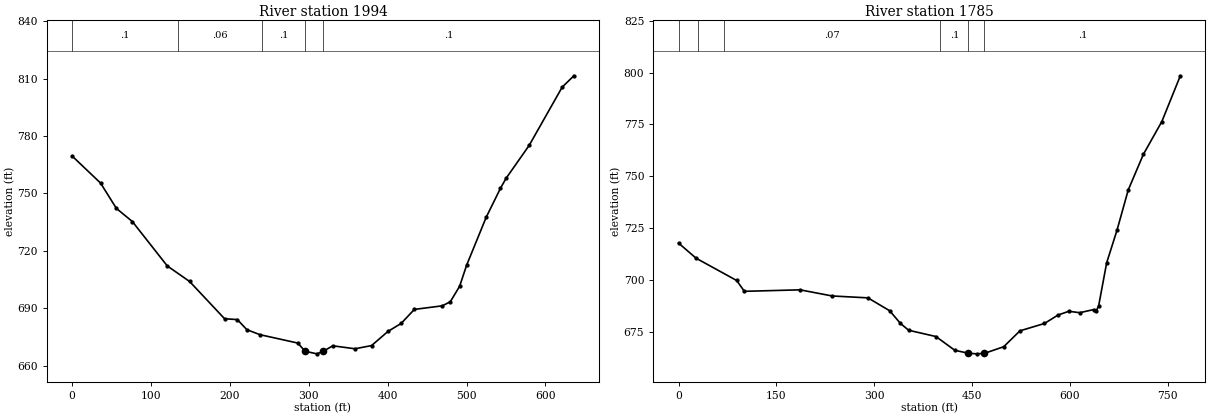
Type RM Length L Ch R = 1 ,1994    ,209.1,209.1,209.1
BEGIN DESCRIPTION:
Structure 2 XS 4
END DESCRIPTION:
XS GIS Cut Line= 6
1610332.35006951394053.9405366781610512.14104851394076.891934335
1610685.73223676394099.0516669151610760.25833443394121.007659748
1610853.90512876 394146.29665117 1610954.2723821394177.475394592
#Sta/Elev= 30
       0  769.61    36.1  755.44    56.2  742.17    76.4  735.32   120.7  712.08
     149  703.95   193.3  684.47   209.5  684.03   221.5  678.76   238.1  676.14
   286.1  671.75   295.3  667.47   310.3  666.11   318.3  667.42   330.4  670.31
   358.7  668.76   379.6  670.44   400.4  677.83   417.1  682.02   433.8  689.35
   469.3  691.23   479.4  693.36   491.2  701.44   500.1  712.49   524.9  737.56
     543  752.73     550  757.87   579.3  775.11   621.2  805.62     636  811.56
#Mann= 5 ,-1,0
       0      .1       0  133.75     .06       0  241.25      .1       0
   295.3    .045       0   318.3      .1       0
Bank Sta=295.3,318.3
XS Rating Curve= 0 ,0
Exp/Cntr(USF)=0,0
Exp/Cntr=0.3,0.1

Type RM Length L Ch R = 1 ,1785    ,96.7,96.7,96.7
BEGIN DESCRIPTION:
Structure 2 XS 3
END DESCRIPTION:
XS GIS Cut Line= 4
1610235.01573646394284.8496857891610288.04771454394382.719275574
1610792.89650046394237.995956944 1610924.1571848 394257.06802219
#Sta/Elev= 30
       0  717.73    26.9  710.41    89.1  699.65   100.9  694.42   186.3  695.14
   235.4  692.18   290.3  691.26   323.6  685.04   340.2  678.89   352.7  675.62
   394.5  672.59   423.5  665.93   444.3  664.53   456.8  664.23   468.9  664.47
   498.4  667.67   523.3  675.34   560.8  678.89   581.6  682.96   598.2  684.78
   614.9   684.1   636.5  685.62   639.7  684.75   643.8  687.23   656.2   708.2
   672.1  723.98   689.3  743.41   712.5  760.59   740.8  776.43   769.1  798.51
#Mann= 6 ,-1,0
       0      .1       0      30     .06       0      70     .07       0
  401.31      .1       0   444.3    .045       0   468.9      .1       0
Bank Sta=444.3,468.9
XS Rating Curve= 0 ,0
Exp/Cntr(USF)=0,0
Exp/Cntr=0.3,0.1