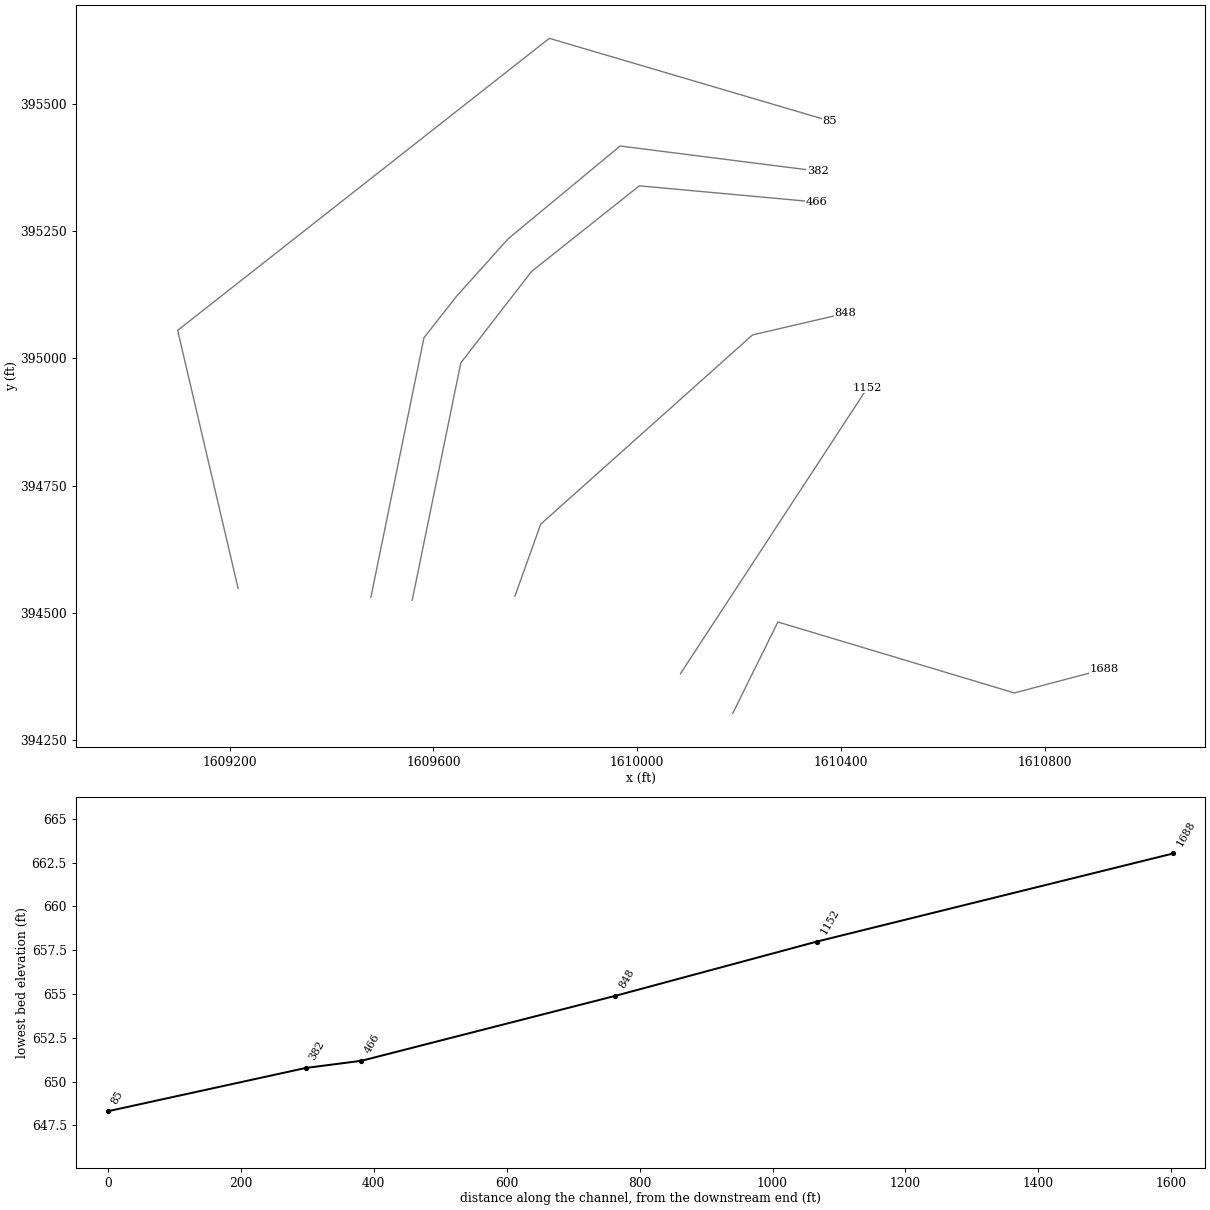
HEC-RAS study STATERN.prj: STATERN

--- STATERN.g01 (geometry) --- (continued)

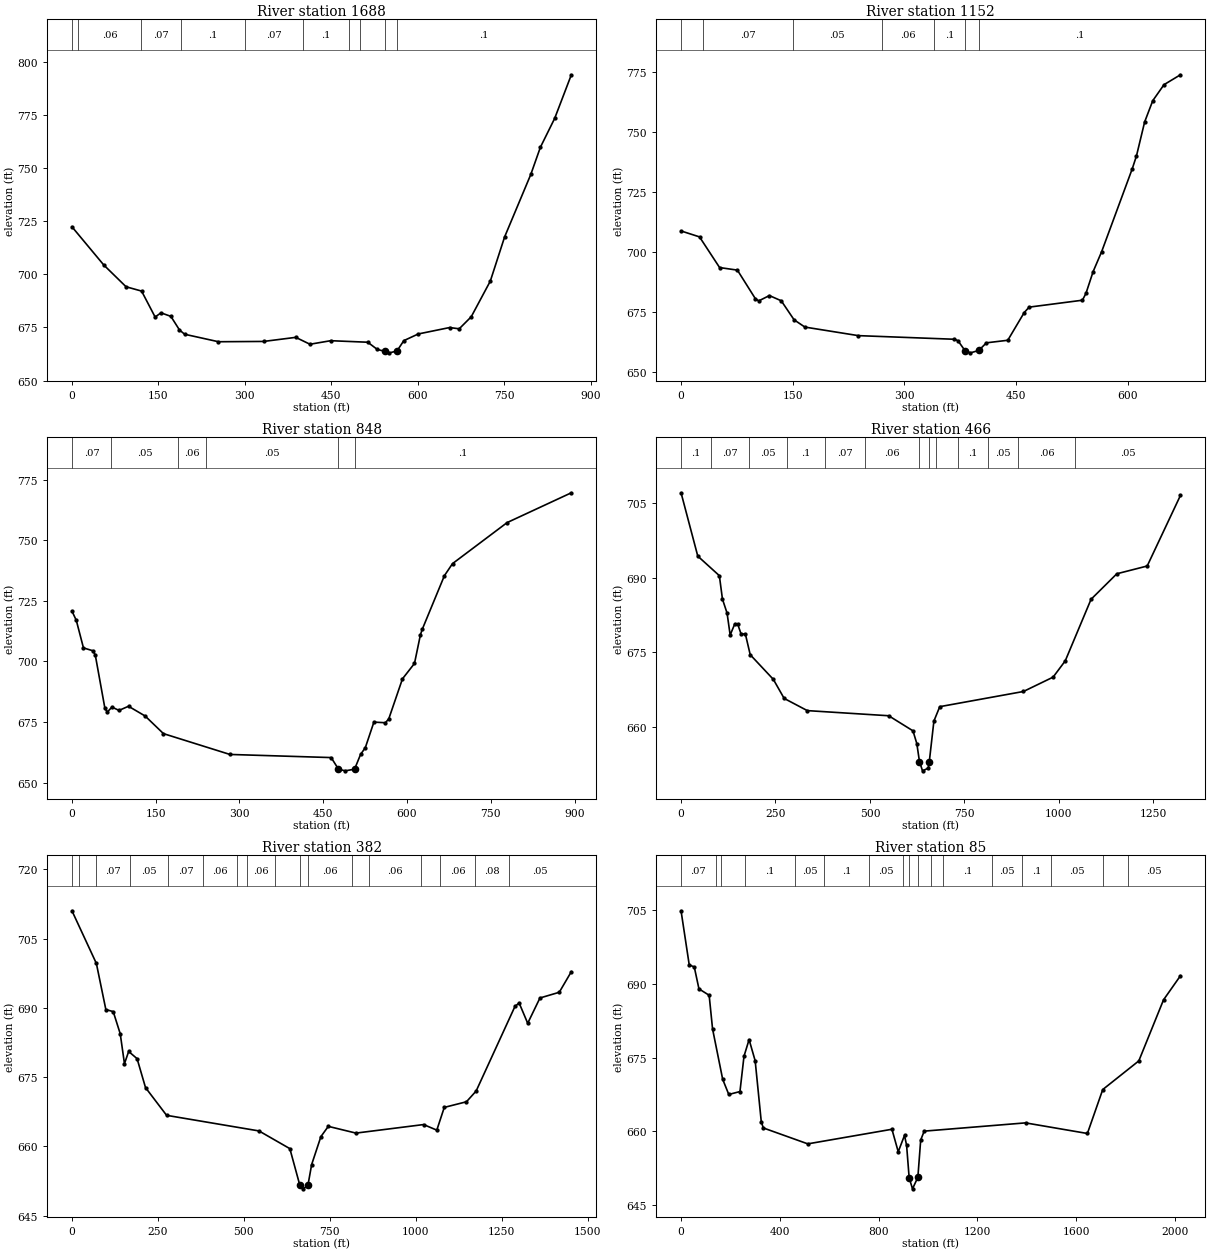
Type RM Length L Ch R = 1 ,1688    ,536.1,536.1,536.1
BEGIN DESCRIPTION:
Structure 2 XS 2
END DESCRIPTION:
XS GIS Cut Line= 4
1610187.71675195394303.1252775131610276.37987734394482.562555084
1610740.80577223394343.2347866171610916.02099621394389.677376106
#Sta/Elev= 30
       0  722.31    55.1  704.37    93.9   694.1   120.8  692.07   144.3  679.86
   154.4  681.85   171.6  680.18   186.5   673.8   195.5  671.77   254.2  668.25
   332.5  668.39   388.2  670.31   412.9  667.07   448.9  668.74   513.1  668.02
   529.8  664.61   542.3  663.78   550.7  663.03   563.8663.8857   575.7  668.77
   600.8  671.91   655.1  674.92   671.8  674.34   692.6  679.98   725.7  696.75
   750.5  717.51     796  746.95   812.6   759.7   837.4  773.29   866.3  793.79
#Mann= 10 ,-1,0
       0      .1       0      10     .06       0     120     .07       0
     190      .1       0  300.15     .07       0  400.15      .1       0
  480.15     .07       0  500.15      .1       0   542.3    .045       0
   563.8      .1       0
Bank Sta=542.3,563.8
XS Rating Curve= 0 ,0
Exp/Cntr(USF)=0,0
Exp/Cntr=0.3,0.1

Type RM Length L Ch R = 1 ,1152    ,303.4,303.4,303.4
BEGIN DESCRIPTION:
Structure 2 XS 1
END DESCRIPTION:
XS GIS Cut Line= 2
1610085.15317587394381.1779389141610452.47183819 394942.71106637
#Sta/Elev= 30
       0  708.72    24.8  706.25    51.8  693.49    75.7  692.42    99.9  680.51
   104.4  679.62   118.7  681.83   134.6  679.67   151.9  671.74   166.4  668.72
   238.2  665.16   367.3  663.65   372.1  663.04   381.6  658.88   388.9     658
     400  658.99   410.3  662.17     439  663.23   461.1  674.77   467.7  677.02
   539.3   679.9   544.1  682.79   553.7  691.83   565.1  700.08   606.3  734.64
   611.9  739.94   622.9  754.09   633.8  762.93   648.9  769.59     671  773.71
#Mann= 7 ,-1,0
       0      .1       0      30     .07       0     150     .05       0
     270     .06       0     340      .1       0   381.6    .045       0
     400      .1       0
Bank Sta=381.6,400
XS Rating Curve= 0 ,0
Exp/Cntr(USF)=0,0
Exp/Cntr=0.3,0.1

Type RM Length L Ch R = 1 ,848     ,382.2,382.2,382.2
BEGIN DESCRIPTION:
Structure 1 XS 4
END DESCRIPTION:
XS GIS Cut Line= 4
1609760.05504945 394533.171868151609810.71969253394674.610663412
1610226.59197113395046.151379322 1610408.1402755395088.371915221
#Sta/Elev= 30
       0  720.79     7.8  716.95    20.6   705.6    37.6  704.41    41.8  702.65
    58.8  680.96    63.1  679.09    71.6  681.19    84.3  679.82   101.3  681.53
     131  677.52   163.9  670.24   282.9  661.66   464.2  660.37   477.3  655.59
   489.3   654.9   506.1  655.58   516.8  661.64   525.4  664.48   540.7  674.99
   561.4  674.74   567.4  676.37   591.9  692.85   613.4  699.19   624.1  711.08
   627.4  713.31     667  735.39   681.5  740.35   779.3  757.28   894.3  769.57
#Mann= 6 ,-1,0
       0     .07       0      70     .05       0  190.24     .06       0
  240.24     .05       0   477.3    .045       0   506.1      .1       0
Bank Sta=477.3,506.1
XS Rating Curve= 0 ,0
Exp/Cntr(USF)=0,0
Exp/Cntr=0.3,0.1

Type RM Length L Ch R = 1 ,466     ,83.9,83.9,83.9
BEGIN DESCRIPTION:
Structure 1 XS 3
END DESCRIPTION:
XS GIS Cut Line= 5
1609558.35277176394525.1740218711609653.91365548394991.395303059
1609792.91130453395170.9339330821610004.30356246395338.889425684
1610351.79768509395307.035797777
#Sta/Elev= 30
       0  707.01    44.3  694.29   101.4  690.37   109.6  685.66   121.8  682.86
     130  678.45   142.3   680.7   150.1   680.6   158.6  678.73   170.4  678.61
   183.1   674.5   244.3  669.55   272.9  665.73   334.2  663.28   549.6  662.25
   613.9  659.22   624.1  656.66   631.1653.0472   639.2  651.19   654.4  651.73
   657.1 653.032   669.3  661.18   684.8  664.07   906.3  667.12   984.8     670
    1017  673.27  1085.3  685.63  1153.5  690.75  1233.9  692.31  1321.9  706.48
#Mann= 13 ,-1,0
       0      .1       0      80     .07       0     180     .05       0
     280      .1       0     380     .07       0  485.91     .06       0
   631.1    .045       0   657.1     .06       0  675.91     .05       0
  732.97      .1       0  812.97     .05       0  892.97     .06       0
 1042.96     .05       0
Bank Sta=631.1,657.1
XS Rating Curve= 0 ,0
Exp/Cntr(USF)=0,0
Exp/Cntr=0.3,0.1

Type RM Length L Ch R = 1 ,382     ,297.6,297.6,297.6
BEGIN DESCRIPTION:
Structure 1 XS 2
END DESCRIPTION:
XS GIS Cut Line= 6
1609477.27080982394530.965590581 1609581.5190466395040.623637098
1609645.22630242395121.7055990441609746.57875485395234.641188897
1609966.65836585395417.0756032751610354.69346944395367.847269236
#Sta/Elev= 30
       0  711.04      71  699.63    98.6  689.63     120  689.19   140.4  684.39
   152.7   677.9   164.9  680.55   189.4  678.99   213.9  672.72   275.2  666.71
   543.8  663.33   633.6  659.49   662.4651.6227   672.7  650.78   686.3   651.6
     697  656.05   723.9   662.1   745.4  664.32   825.8  662.86  1022.5  664.71
  1060.9   663.5  1082.6  668.43  1147.1  669.65  1175.3  671.98  1288.2  690.32
  1300.3  691.06  1325.2  686.66  1360.8  692.14    1417  693.38  1452.1  697.85
#Mann= 17 ,-1,0
       0     .06       0      20      .1       0      70     .07       0
     170     .05       0     280     .07       0     380     .06       0
     480     .05       0     510     .06       0  590.21      .1       0
   662.4    .045       0   686.3     .06       0  815.07      .1       0
  865.07     .06       0 1015.07     .05       0 1070.93     .06       0
 1170.93     .08       0 1270.93     .05       0
Bank Sta=662.4,686.3
XS Rating Curve= 0 ,0
Exp/Cntr(USF)=0,0
Exp/Cntr=0.3,0.1

Type RM Length L Ch R = 1 ,85      ,,,
BEGIN DESCRIPTION:
Structure 1 XS 1
END DESCRIPTION:
XS GIS Cut Line= 4
1609216.65021785394548.3402967121609097.92305928395055.102558874
 1609827.6607168395628.4678612051610377.85974429395466.303937313
#Sta/Elev= 30
       0  704.88    33.1  693.88    53.6  693.44    72.5  688.99   113.8  687.69
   127.6  680.84   168.6  670.59   193.3  667.51   238.5   668.1   254.9  675.29
   275.5  678.67   300.1  674.37   324.8  661.97     333   660.7   513.2  657.46
   853.9  660.43   879.4  655.85   904.8  659.19   913.3  657.16   923.6650.5613
   937.2  648.31   958.9  650.66   970.3  658.24   984.6  660.05  1394.8  661.73
  1645.3  659.57  1707.5  668.51  1853.5  674.34  1953.6  686.76  2022.1  691.66
#Mann= 17 ,-1,0
       0     .07       0     140     .06       0     160     .05       0
     260      .1       0     460     .05       0  580.48      .1       0
  760.48     .05       0  900.48      .1       0   923.6    .045       0
   958.9      .1       0 1010.48     .05       0 1060.48      .1       0
 1260.48     .05       0 1380.48      .1       0 1498.53     .05       0
 1708.53     .06       0 1808.53     .05       0
Bank Sta=923.6,958.9
XS Rating Curve= 0 ,0
Exp/Cntr(USF)=0,0
Exp/Cntr=0.3,0.1
LCMann Table=0

Chan Stop Cuts=-1
Use User Specified Reach Order=0
Composite Channel Slope=5